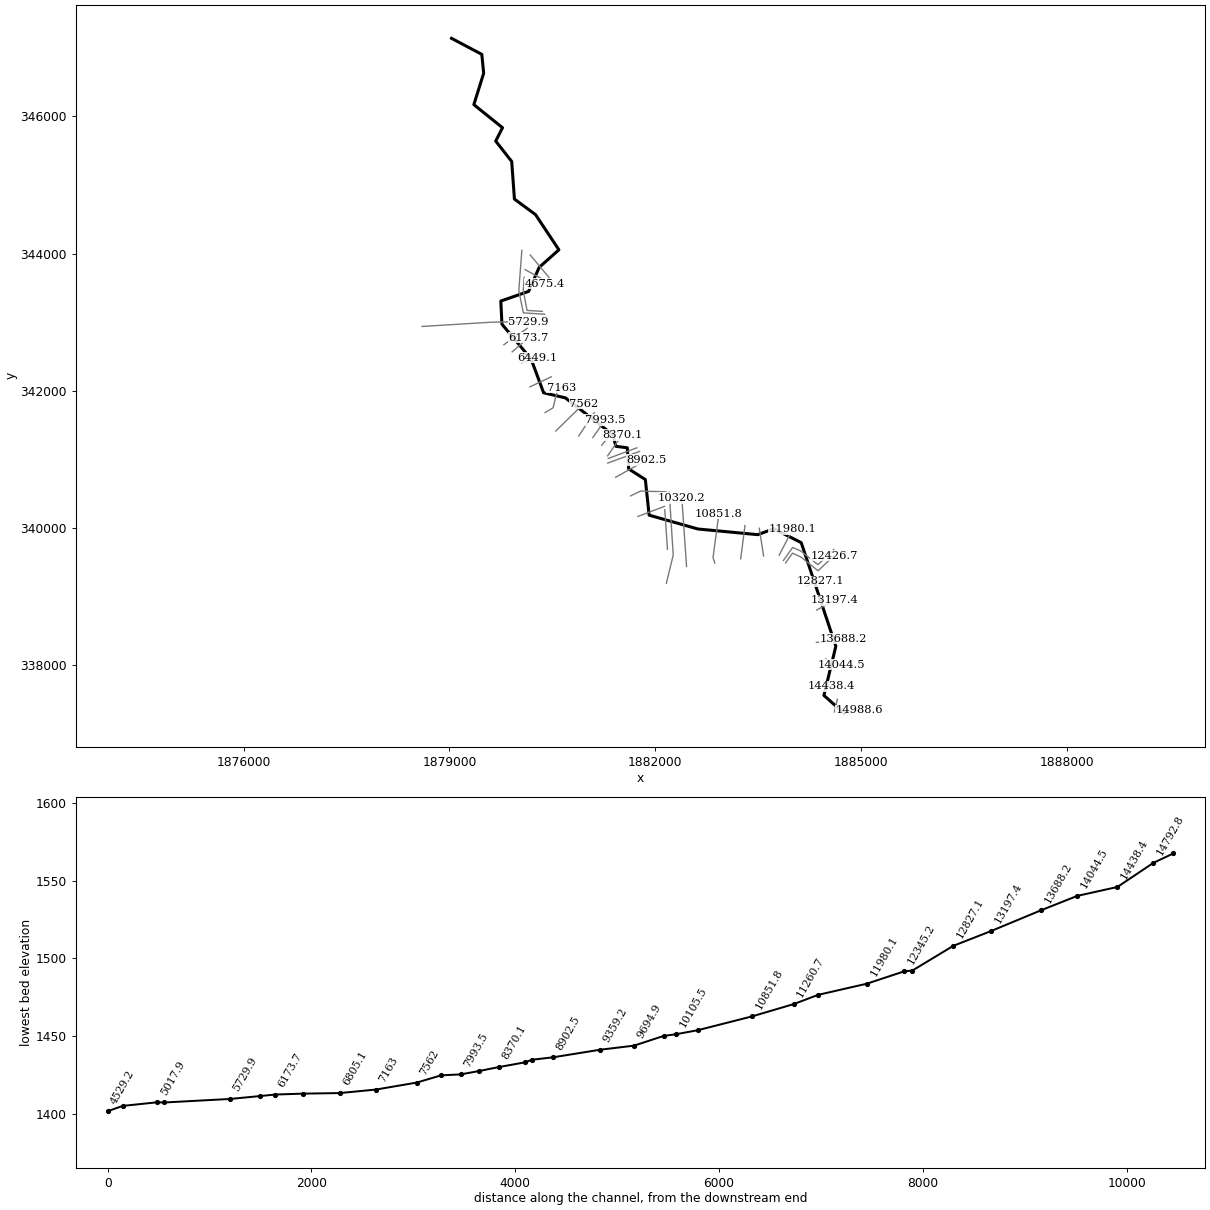
--- BIRDSCK.prj (project) ---

Proj Title=BIRDSCK
Current Plan=p01
Geom File=g01
Flow File=f01
Plan File=p01
DSS Export Rating Curves=0
DSS Export Rating Curve Sorted=0
DSS Export Volume Flow Curves=0
DXF OffsetX=0
DXF OffsetY=0
DXF ScaleX=0
DXF ScaleY=0

--- BIRDSCK.p01 (plan) ---

Plan Title=Floodplain
Program Version=4.00
Geom File=g01
Flow File=f01
K Sum by GR=0
Std Step Tol=0.01
Critical Tol=0.01
Num of Std Step Trials=20
Max Error Tol=0.3
Flow Tol Ratio=0.001
Split Flow NTrial=30
Split Flow Tol=0.02
Split Flow Ratio=0.02
Log Output Level=0
Friction Slope Method=1
Unsteady Friction Slope Method=2
Unsteady Bridges Friction Slope Method=1
Global Log Level=0
CheckData=False
Run HTab=0
Run UNet=0
Run PostProcess=0
UNET Theta=0
UNET Theta Warmup=0
UNET ZTol=0
UNET ZSATol=0
UNET MxIter=0
UNET MaxInSteps=0
UNET DtIC=0
UNET DtMin=0
UNET MaxCRTS=0
UNET WFStab=0
UNET SFStab=0
UNET WFX=0
UNET SFX=0
UNET DSS MLevel=0
UNET DZMax Abort=0
UNET Convert EG Bridges=0
UNET Use Existing IB Tables=0
UNET Froude Limit=0
UNET Froude Power=0
Write IC File=0
Echo Input=False
Echo Output=False
Write Detailed=0

--- BIRDSCK.f01 (steady flow) ---

Flow Title=NFF Regression Equation
Program Version=4.10
Number of Profiles= 1
Profile Names=P100yr
River Rch & RM=BIRDSCK,Main            ,14988.6
517.5213
River Rch & RM=BIRDSCK,Main            ,14438.4
722.2348
River Rch & RM=BIRDSCK,Main            ,11980.1
749.6796
River Rch & RM=BIRDSCK,Main            ,11500.5
 983.764
River Rch & RM=BIRDSCK,Main            ,10320.2
1016.742
River Rch & RM=BIRDSCK,Main            ,9984.5
1264.666
River Rch & RM=BIRDSCK,Main            ,4675.4
 1369.67
River Rch & RM=BIRDSCK,Main            ,3677.8
1428.406
River Rch & RM=BIRDSCK,Main            ,255.3
1475.921
Boundary for River Rch & Prof#=BIRDSCK,Main            , 1
Up Type= 0
Dn Type= 3
Dn Slope=0.02567
DSS Import GetInterval= 0
DSS Import GetPeak= 0
DSS Import FillOption= 0

--- BIRDSCK.g01 (geometry) ---

Geom Title=USGS 10m DEM
Program Version=4.10

River Reach=BIRDSCK         ,Main
Reach XY= 30
     1884755.238      337299.181     1884459.235      337560.457
     1884632.868      338277.478     1884128.506      339786.927
     1883728.324      339989.333     1883495.159      339903.343
     1882622.034      339986.026     1881911.213      340187.736
     1881856.396      340706.354     1881613.309      340861.797
     1881593.466      341169.375     1881426.447      341190.873
     1881383.453      341358.883     1880691.288       341896.65
     1880373.456      341970.799     1880191.174      342462.692
     1879766.186      342970.362      1879749.65      343307.706
     1880154.793      343448.266     1880308.582      343798.177
     1880596.317      344054.492     1880255.666      344567.123
      1879948.21      344793.512       1879908.4      345341.691
     1879675.236      345638.686     1879774.455      345833.816
     1879356.652      346169.654     1879499.949      346627.567
     1879472.767      346902.346     1879031.332      347135.875

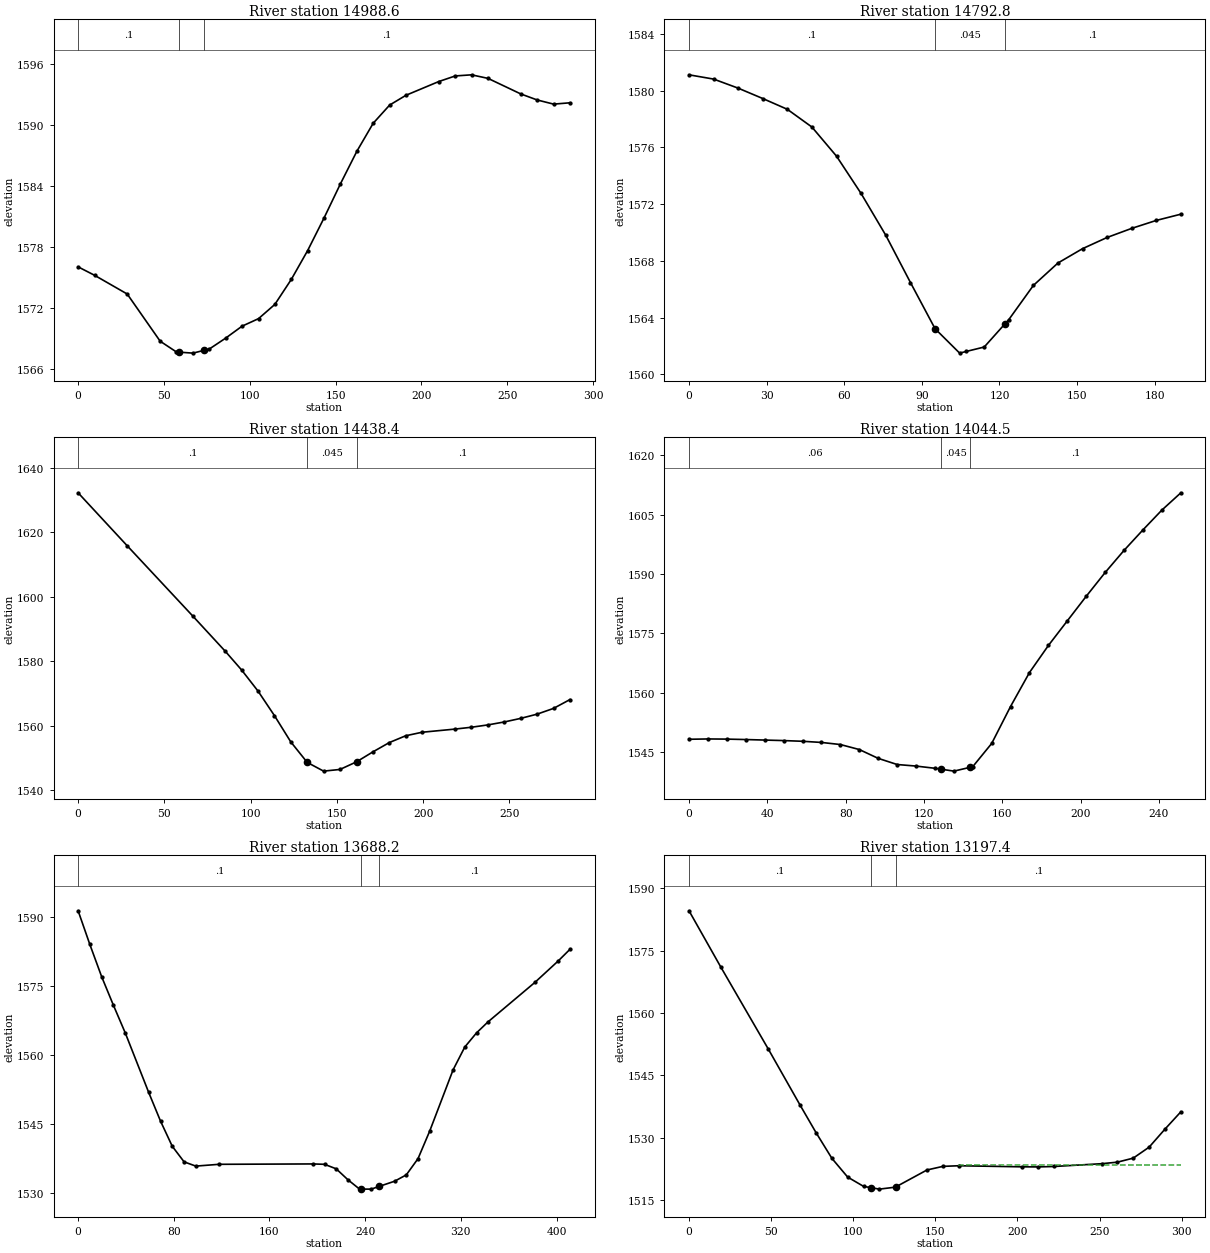
Type RM Length L Ch R = 1 ,14988.6 ,163.8,195.8,225.7
XS GIS Cut Line= 2
     1884686.258      337307.085     1884970.112      337346.147
#Sta/Elev= 29
       0 1576.01     9.6 1575.18    28.6 1573.34    47.8  1568.7    57.3 1567.64
    58.5 1567.63    66.9 1567.53    73.5 1567.81    76.4 1567.93      86 1569.01
    95.5 1570.18   105.1 1570.92   114.6 1572.32   124.2 1574.78   133.7 1577.61
   143.3 1580.83   152.8 1584.17   162.4 1587.38   171.9 1590.13   181.5 1591.92
     191 1592.88   210.1 1594.23   219.7 1594.78   229.2 1594.89   238.8 1594.54
   257.9 1593.01   267.4 1592.42     277 1592.01   286.5 1592.14
#Mann= 3 , 0 , 0
       0      .1       0    58.5    .045       0    73.5      .1       0
Bank Sta=58.5,73.5
XS Rating Curve= 0 ,0
Exp/Cntr=0.3,0.1

Type RM Length L Ch R = 1 ,14792.8 ,384.7,354.4,323.3
XS GIS Cut Line= 2
     1884610.737      337320.105     1884655.008      337505.001
#Sta/Elev= 23
       0 1581.11     9.5 1580.81      19 1580.17    28.5 1579.44      38 1578.68
    47.5 1577.43      57 1575.38    66.5 1572.75      76 1569.82    85.6 1566.47
    95.1 1563.22   104.6  1561.5   107.2 1561.62   114.1 1561.93   122.2 1563.58
   123.6 1563.86   133.1 1566.27   142.6 1567.85   152.1 1568.86   161.6 1569.65
   171.1 1570.29   180.6 1570.85   190.1 1571.29
#Mann= 3 , 0 , 0
       0      .1       0    95.1    .045       0   122.2      .1       0
Bank Sta=95.1,122.2
XS Rating Curve= 0 ,0
Exp/Cntr=0.3,0.1

Type RM Length L Ch R = 1 ,14438.4 ,401.7,393.9,386.1
XS GIS Cut Line= 3
     1884287.821       337666.46     1884418.029      337692.501
     1884570.336      337691.235
#Sta/Elev= 24
       0 1632.19    28.4 1615.81    66.4 1594.04    85.4 1583.03    94.8 1577.27
   104.3 1570.74   113.8 1563.15   123.3 1554.99   132.8 1548.65   142.3 1545.94
   151.8 1546.46   161.4 1548.82   170.9 1551.91   180.4 1554.79   189.9  1556.9
   199.4 1557.99   218.5 1558.97     228 1559.54   237.5 1560.26     247 1561.17
   256.5 1562.28   266.1  1563.6   275.6 1565.38   285.1 1568.11
#Mann= 3 , 0 , 0
       0      .1       0   132.8    .045       0   161.4      .1       0
Bank Sta=132.8,161.4
XS Rating Curve= 0 ,0
Exp/Cntr=0.3,0.1

Type RM Length L Ch R = 1 ,14044.5 ,340.2,356.3,372.4
XS GIS Cut Line= 2
     1884483.133      338090.939     1884720.112      338007.605
#Sta/Elev= 29
       0 1548.27     9.7 1548.35    19.3 1548.31      29  1548.2    38.6 1548.07
    48.3 1547.94      58 1547.76    67.6 1547.47    77.3 1546.94      87 1545.67
    96.6 1543.45   106.3 1541.89   115.9  1541.5   125.6 1540.94   128.7 1540.71
   135.3 1540.22   143.7  1541.2   144.9 1541.34   154.6 1547.22   164.2 1556.53
   173.9 1565.14   183.6    1572   193.2 1578.18   202.9 1584.41   212.6 1590.44
   222.2    1596   231.9  1601.2   241.5 1606.17   251.2 1610.54
#Mann= 3 , 0 , 0
       0     .06       0   128.7    .045       0   143.7      .1       0
Bank Sta=128.7,143.7
XS Rating Curve= 0 ,0
Exp/Cntr=0.3,0.1

Type RM Length L Ch R = 1 ,13688.2 ,488,490.8,493.6
XS GIS Cut Line= 4
     1884350.321       338335.73     1884438.862      338333.126
     1884639.383      338411.251      1884743.55       338385.21
#Sta/Elev= 30
       0 1591.26     9.8 1583.97    19.7 1576.96    29.5  1570.8    39.4  1564.8
      59  1551.9    68.9 1545.68    78.7 1540.23    88.6 1536.85    98.4 1535.93
   117.9 1536.32   196.2  1536.4     206 1536.32   215.8 1535.34   225.5 1532.99
   235.3 1530.95   236.7 1530.95   245.1 1530.94   251.7 1531.53   264.6 1532.65
   274.4 1534.03   284.2 1537.55     294 1543.54   313.5 1556.78   323.3 1561.74
   333.1  1564.8   342.8 1567.21   381.9 1575.74   401.4 1580.39   411.2 1582.91
#Mann= 3 , 0 , 0
       0      .1       0   236.7    .045       0   251.7      .1       0
Bank Sta=236.7,251.7
XS Rating Curve= 0 ,0
Exp/Cntr=0.3,0.1

Type RM Length L Ch R = 1 ,13197.4 ,377.5,370.3,366.5
XS GIS Cut Line= 2
     1884352.925       338804.48     1884615.946       338947.71
#Sta/Elev= 24
       0  1584.6    19.3 1571.09    48.3 1551.29    67.6 1537.83    77.3 1531.21
      87 1524.99    96.6 1520.48   106.3 1518.24     111 1517.92   115.9 1517.58
   125.6 1518.05     126 1518.13   144.9 1522.19   154.6 1523.06   164.2 1523.21
   202.9 1522.95   212.5 1522.93   222.2 1523.03   251.2  1523.7   260.8 1524.07
   270.5 1525.04   280.2 1527.69   289.8 1532.01   299.5 1536.19
#Mann= 3 , 0 , 0
       0      .1       0     111    .045       0     126      .1       0
#XS Ineff= 2 , 0
                          164.37         1523.35
Permanent Ineff=
       F       F
Bank Sta=111,126
XS Rating Curve= 0 ,0
Exp/Cntr=0.3,0.1

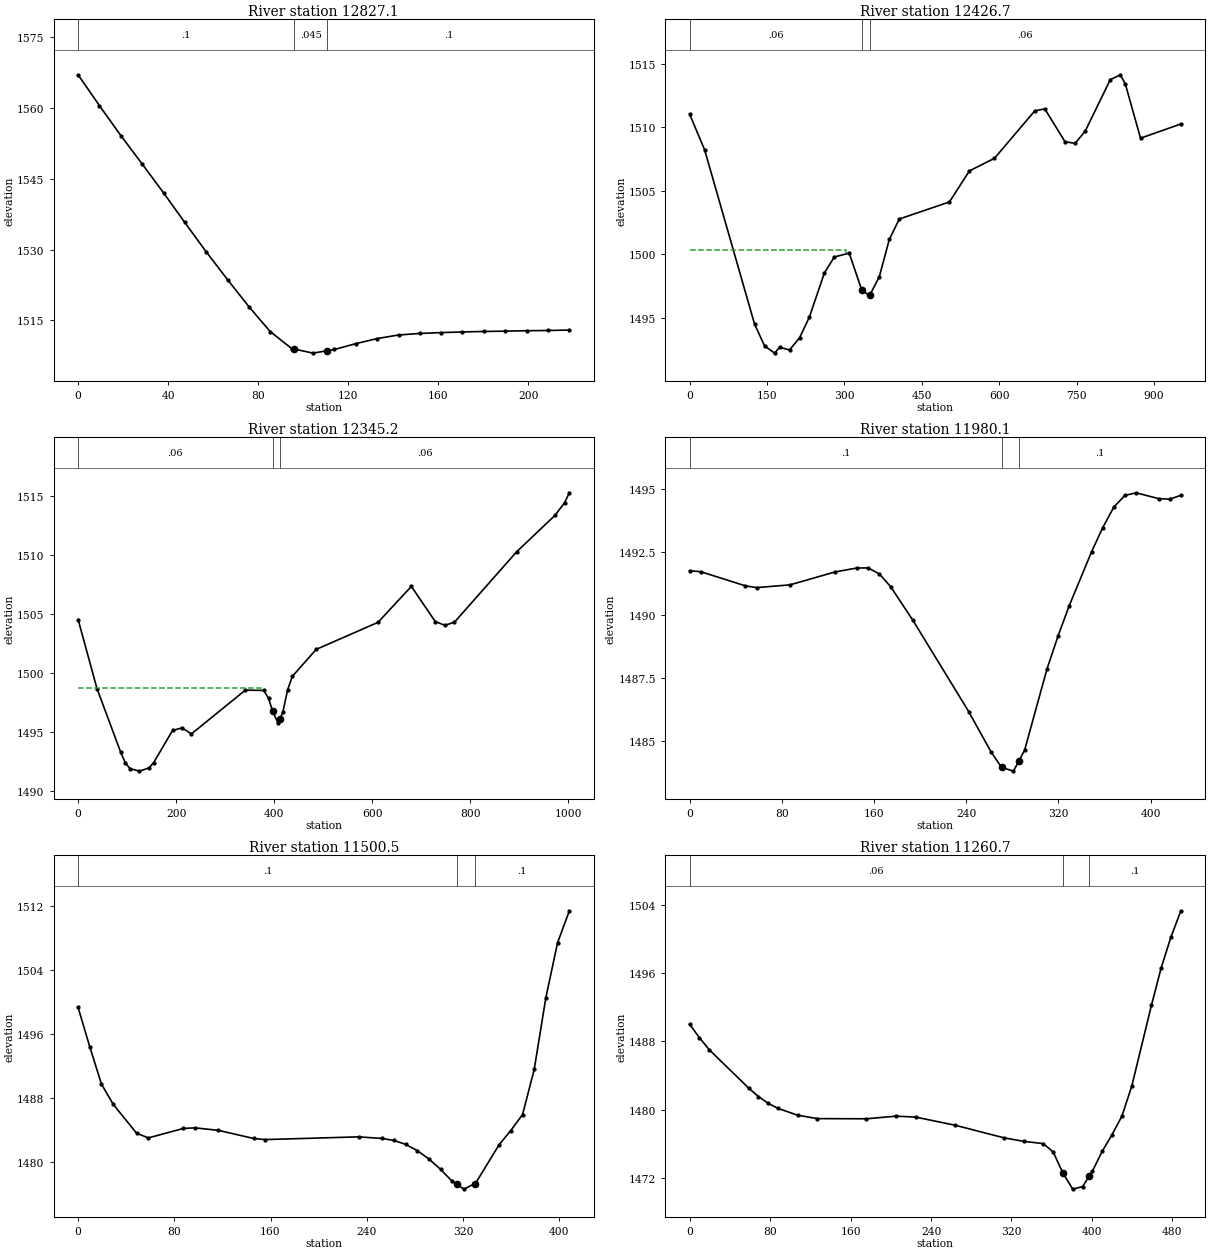
Type RM Length L Ch R = 1 ,12827.1 ,427.1,400.3,371.9
XS GIS Cut Line= 2
     1884196.675      339153.439     1884402.404      339226.355
#Sta/Elev= 26
       0 1567.07     9.5 1560.53      19 1554.19    28.5 1548.15      38 1542.04
    47.4 1535.78    56.9 1529.57    66.4 1523.67    75.9 1517.93    85.4 1512.63
    94.9 1509.06    95.8 1508.97   104.4 1508.08   110.8  1508.6   113.9 1508.85
   123.4 1510.09   132.9 1511.17   142.4 1511.92   151.8 1512.25   161.3 1512.43
   170.8 1512.57   180.3 1512.67   189.8 1512.74   199.3 1512.83   208.8 1512.88
   218.3 1512.97
#Mann= 3 , 0 , 0
       0      .1       0    95.8    .045       0   110.8      .1       0
Bank Sta=95.8,110.8
XS Rating Curve= 0 ,0
Exp/Cntr=0.3,0.1

Type RM Length L Ch R = 1 ,12426.7 ,80.6,81.5,86
XS GIS Cut Line= 5
     1883900.197      339491.582     1884000.892      339633.943
     1884123.758      339577.918     1884373.758      339377.397
     1884608.133      339598.751
#Sta/Elev= 30
       0 1511.04    29.1 1508.23   125.9 1494.51   145.3  1492.8   164.7 1492.23
   174.4 1492.69   193.7 1492.48     213 1493.43   232.2 1495.07   261.2 1498.54
   280.5  1499.8   309.4  1500.1   333.9 1497.17   348.9 1496.77   367.7 1498.24
   387.1 1501.18   406.5 1502.79   503.6 1504.13   542.5 1506.58     591 1507.57
     669  1511.3   688.5 1511.46   727.6 1508.88   747.1 1508.74   766.7 1509.69
   815.5 1513.76     835 1514.14   844.8  1513.4   874.1 1509.15   952.3 1510.27
#Mann= 3 , 0 , 0
       0     .06       0   333.9    .045       0   348.9     .06       0
#XS Ineff= 2 , 0
          302.82 1500.31
Permanent Ineff=
       F       F
Bank Sta=333.9,348.9
XS Rating Curve= 0 ,0
Exp/Cntr=0.3,0.1

Type RM Length L Ch R = 1 ,12345.2 ,322,365.1,406
XS GIS Cut Line= 5
     1883868.947       339528.04      1884003.01      339716.444
     1884121.154       339666.46     1884371.154      339465.939
     1884605.529      339687.293
#Sta/Elev= 30
       0 1504.53    38.5 1498.69    86.7 1493.32    96.4  1492.4     106 1491.91
   125.2  1491.7   144.5 1491.97   154.2 1492.42   192.7 1495.14     212 1495.36
   231.2 1494.85   341.2 1498.55   378.9 1498.53   388.6 1497.85   396.8  1496.8
   408.1 1495.74   411.8  1496.1   417.8 1496.69   427.5 1498.58   437.2 1499.72
   485.8    1502     612 1504.29     680 1507.33   728.8 1504.36   748.4 1504.04
   767.9  1504.3   894.9 1510.26   973.1 1513.34   992.6 1514.41  1002.4 1515.25
#Mann= 3 , 0 , 0
       0     .06       0   396.8    .045       0   411.8     .06       0
#XS Ineff= 2 , 0
          373.52 1498.77
Permanent Ineff=
       F       F
Bank Sta=396.8,411.8
XS Rating Curve= 0 ,0
Exp/Cntr=0.3,0.1

Type RM Length L Ch R = 1 ,11980.1 ,464.1,479.6,494.8
XS GIS Cut Line= 2
      1883806.05       339603.96     1884003.966      339981.564
#Sta/Elev= 28
       0 1491.74     9.7  1491.7    48.4 1491.14    58.1 1491.07    87.2 1491.18
     126 1491.69   145.3 1491.85     155 1491.85   164.7 1491.61   174.4 1491.11
   193.8 1489.77   242.2 1486.15   261.6 1484.55   270.7 1483.94     281 1483.79
   285.7 1484.19   290.7 1484.62   310.1 1487.84   319.8 1489.16   329.4 1490.35
   348.8 1492.49   358.5 1493.45   368.2 1494.27   377.9 1494.73   387.6 1494.83
     407  1494.6   416.6 1494.58   426.3 1494.73
#Mann= 3 , 0 , 0
       0      .1       0   270.7    .045       0   285.7      .1       0
Bank Sta=270.7,285.7
XS Rating Curve= 0 ,0
Exp/Cntr=0.3,0.1

Type RM Length L Ch R = 1 ,11500.5 ,246.2,239.9,233.6
XS GIS Cut Line= 2
     1883579.487      339593.543     1883516.987      339997.189
#Sta/Elev= 30
       0 1499.32     9.7  1494.4    19.4 1489.74    29.2  1487.2    48.6 1483.59
    58.4    1483    87.5 1484.18    97.2 1484.26   116.7 1483.94   145.9 1482.93
   155.6 1482.79   233.4 1483.13   252.8 1482.93   262.6 1482.68   272.3  1482.2
     282 1481.41   291.8 1480.36   301.5 1479.05   311.2 1477.55   314.7  1477.2
   320.9 1476.59   329.7 1477.27   330.6 1477.34   350.1 1482.14   359.8 1483.92
   369.6 1485.92   379.3 1491.56     389 1500.56   398.7  1507.4   408.5 1511.41
#Mann= 3 , 0 , 0
       0      .1       0   314.7    .045       0   329.7      .1       0
Bank Sta=314.7,329.7
XS Rating Curve= 0 ,0
Exp/Cntr=0.3,0.1

Type RM Length L Ch R = 1 ,11260.7 ,409,408.9,408.7
XS GIS Cut Line= 2
     1883246.154      339551.876     1883308.654      340036.251
#Sta/Elev= 30
       0 1490.03     9.8 1488.43    19.5 1487.03    58.6 1482.53    68.4 1481.53
    78.1 1480.73    87.9 1480.13   107.4 1479.33     127 1478.93   175.8 1478.91
   205.1 1479.22   224.7 1479.11   263.7 1478.16   312.6 1476.67   332.1 1476.26
   351.6 1475.99   361.4 1475.02   371.2 1472.52   380.9 1470.64   390.7 1470.94
   397.1 1472.14   400.5 1472.77   410.2 1475.08     420 1477.04   429.8 1479.22
   439.6 1482.75   459.1 1492.23   468.8 1496.64   478.6  1500.3   488.4 1503.36
#Mann= 3 , 0 , 0
       0     .06       0   371.2    .045       0   397.1      .1       0
Bank Sta=371.2,397.1
XS Rating Curve= 0 ,0
Exp/Cntr=0.3,0.1

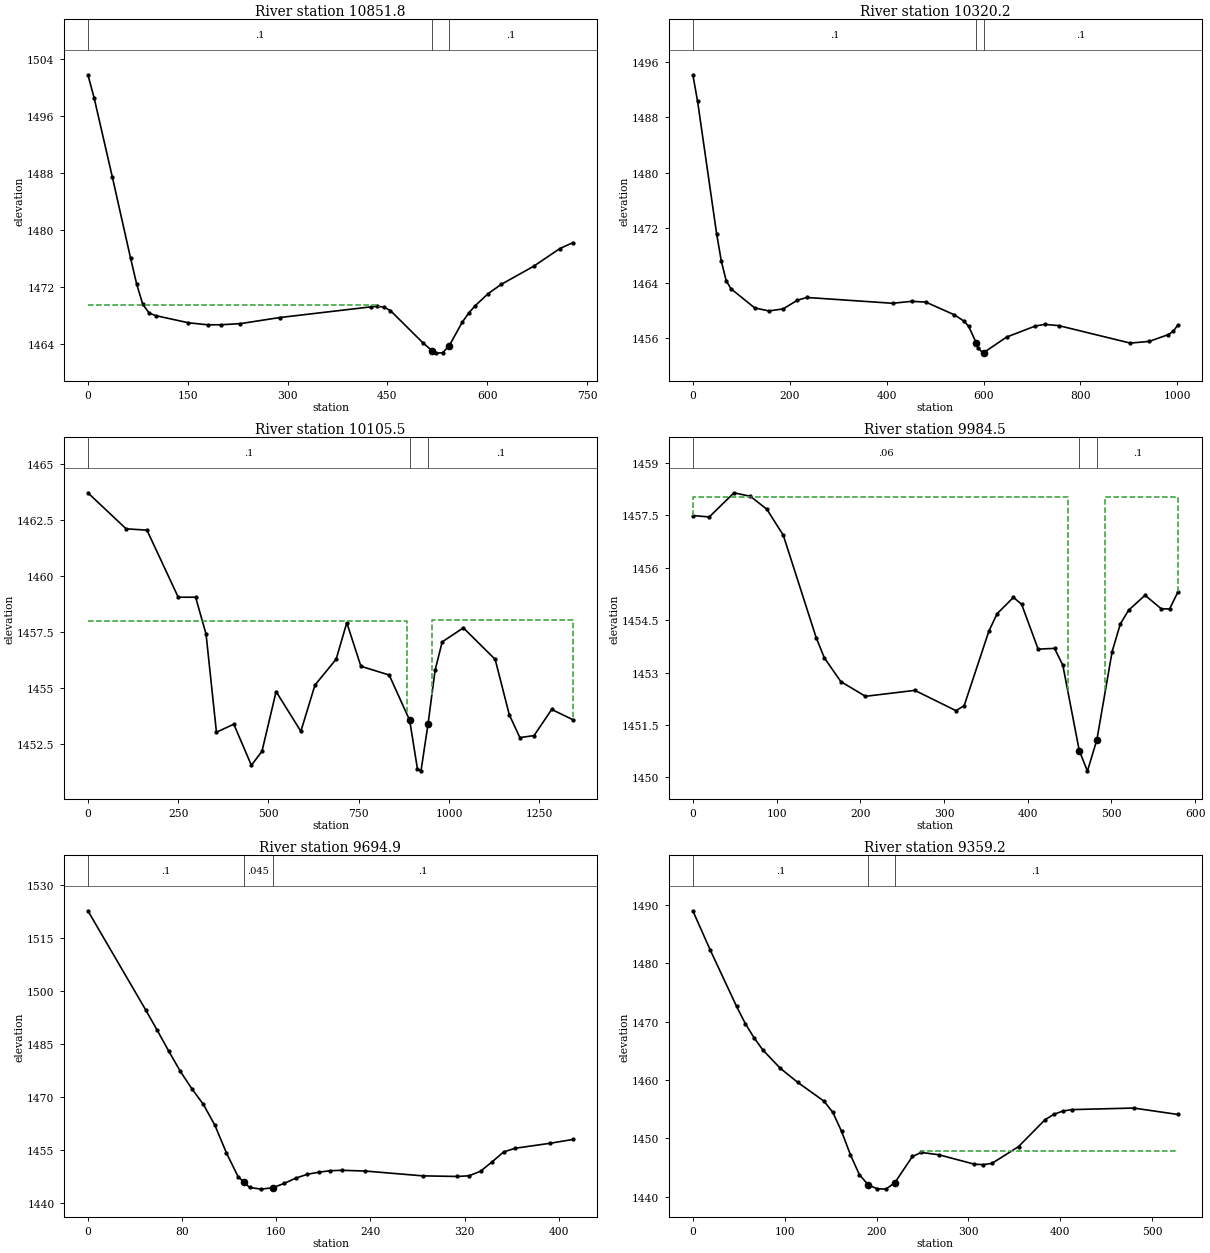
Type RM Length L Ch R = 1 ,10851.8 ,526.3,531.6,536.3
XS GIS Cut Line= 3
      1882868.55      339489.376     1882842.508      339567.501
     1882928.446      340208.126
#Sta/Elev= 30
       0 1501.78     9.2 1498.59    36.6 1487.48      64  1476.1    73.2 1472.45
    82.4 1469.59    92.1 1468.35   101.9    1468   150.9    1467   180.3 1466.71
   199.9 1466.72   229.2 1466.88     288 1467.73   425.1 1469.23   434.9  1469.3
   444.7  1469.2   454.5 1468.71   503.5 1464.17   517.2 1463.07     523 1462.74
   532.8 1462.79   542.6 1463.73   562.2 1467.04     572 1468.34   581.8 1469.38
   601.4 1471.09     621 1472.38     670 1474.94   709.1 1477.41   728.7 1478.24
#Mann= 3 , 0 , 0
       0      .1       0   517.2    .045       0   542.6      .1       0
#XS Ineff= 2 , 0
          437.18 1469.52
Permanent Ineff=
       F       F
Bank Sta=517.2,542.6
XS Rating Curve= 0 ,0
Exp/Cntr=0.3,0.1

Type RM Length L Ch R = 1 ,10320.2 ,217.2,214.7,243.7
XS GIS Cut Line= 2
     1882457.091      339439.897     1882388.097       340438.61
#Sta/Elev= 30
       0 1494.13     9.8 1490.28    49.1 1471.13    58.9 1467.14    68.7 1464.38
    78.5  1463.2   127.6 1460.42     157 1459.98   186.5 1460.28   215.9 1461.54
   235.6 1461.93   412.2 1461.09   451.5 1461.37   480.9 1461.26   539.8 1459.42
   559.4 1458.52   569.2 1457.78   585.3  1455.3   588.9 1454.67   598.7 1453.88
   600.3 1453.95   647.8 1456.21   706.6 1457.79   726.3 1458.04   755.7 1457.85
     903 1455.33   942.2 1455.58   981.5 1456.56   991.3 1457.01  1001.1 1457.94
#Mann= 3 , 0 , 0
       0      .1       0   585.3    .045       0   600.3      .1       0
Bank Sta=585.3,600.3
XS Rating Curve= 0 ,0
Exp/Cntr=0.3,0.1

Type RM Length L Ch R = 1 ,10105.5 ,118.6,121,112.9
XS GIS Cut Line= 3
      1882162.35      339194.707     1882262.635      339605.914
     1882204.069      340523.679
#Sta/Elev= 30
       0 1463.73   105.8 1462.12   163.5 1462.06   250.1 1459.06   298.2 1459.06
   327.1 1457.41   355.9 1453.02     404 1453.38   452.6 1451.54     482 1452.17
   521.1 1454.84   589.6 1453.06   628.7 1455.13   687.4 1456.29   716.8 1457.92
   755.9 1455.97   834.2 1455.58     891 1453.55   912.4 1451.38   922.2 1451.28
   941.8 1453.39   961.3 1455.79   980.9 1457.06  1039.6 1457.69  1127.7 1456.28
  1166.8  1453.8  1196.1 1452.78  1235.3 1452.87  1284.2 1454.04  1342.9 1453.58
#Mann= 3 , 0 , 0
       0      .1       0     891    .045       0   941.8      .1       0
#XS Ineff= 2 , 0
          883.38 1458.01  952.39         1458.05
Permanent Ineff=
       F       F
Bank Sta=891,941.8
XS Rating Curve= 0 ,0
Exp/Cntr=0.3,0.1

Type RM Length L Ch R = 1 ,9984.5  ,323.2,289.7,257
XS GIS Cut Line= 2
     1882178.446      339689.897     1882139.383      340268.022
#Sta/Elev= 30
       0 1457.49    19.6 1457.45    49.1 1458.14    68.8 1458.04    88.4 1457.67
     108 1456.93   147.3    1454   157.1 1453.42   176.8 1452.74   206.2 1452.32
   265.2 1452.49   314.3 1451.91   324.1 1452.05   353.6 1454.18   363.4 1454.68
     383 1455.15   392.8 1454.95   412.5 1453.67   432.1 1453.69     442 1453.21
   461.6 1450.77   471.4 1450.18   482.7 1451.08   500.9  1453.6   510.7 1454.39
   520.5 1454.78   540.2 1455.21   559.8 1454.82   569.6 1454.82   579.4  1455.3
#Mann= 3 , 0 , 0
       0     .06       0   461.6    .045       0   482.7      .1       0
#XS Ineff= 2 , 0
          448.73 1458.01  492.68         1458.01
Permanent Ineff=
       F       F
Bank Sta=461.6,482.7
XS Rating Curve= 0 ,0
Exp/Cntr=0.3,0.1

Type RM Length L Ch R = 1 ,9694.9  ,343.8,335.6,327.4
XS GIS Cut Line= 2
     1881748.758      340169.064     1882134.175      340314.897
#Sta/Elev= 30
       0 1522.82    49.1 1494.74    58.9 1488.98    68.7 1483.05    78.5 1477.35
    88.3 1472.42    98.1 1467.97   107.9 1462.06   117.7 1454.22   127.6  1447.5
   132.5 1445.96   137.4 1444.43   147.2 1443.96     157 1444.36   166.8 1445.58
   176.6 1447.07   186.4 1448.16   196.2 1448.76     206 1449.18   215.8 1449.29
   235.5 1449.09   284.5 1447.72     314 1447.55   323.8 1447.74   333.6 1449.02
   343.4 1451.68   353.2 1454.48     363 1455.54   392.5 1456.94   412.1 1458.04
#Mann= 3 , 0 , 0
       0      .1       0   132.5    .045       0     157      .1       0
Bank Sta=132.5,157
XS Rating Curve= 0 ,0
Exp/Cntr=0.3,0.1

Type RM Length L Ch R = 1 ,9359.2  ,444.6,456.7,468.7
XS GIS Cut Line= 3
     1881641.987      340468.543     1881787.821      340538.855
     1882153.669       340528.04
#Sta/Elev= 30
       0 1488.95      19 1482.21    47.6 1472.59    57.1 1469.64    66.7  1467.2
    76.2 1465.13    95.2 1461.99   114.3 1459.57   142.8 1456.36   152.4 1454.44
   161.9 1451.19   171.5  1447.2   181.2  1443.8   190.8 1442.06   200.4 1441.38
   210.1 1441.31   219.7 1442.38     239  1446.9   248.6 1447.59   267.8 1447.19
   306.4 1445.58     316  1445.5   325.6 1445.72   354.5 1448.59   383.4  1453.2
   393.1 1454.12   402.7 1454.67   412.3 1454.92   479.8 1455.19   527.9 1454.09
#Mann= 3 , 0 , 0
       0      .1       0   190.8    .045       0   219.7      .1       0
#XS Ineff= 2 , 0
                          248.45         1447.86
Permanent Ineff=
       F       F
Bank Sta=190.8,219.7
XS Rating Curve= 0 ,0
Exp/Cntr=0.3,0.1

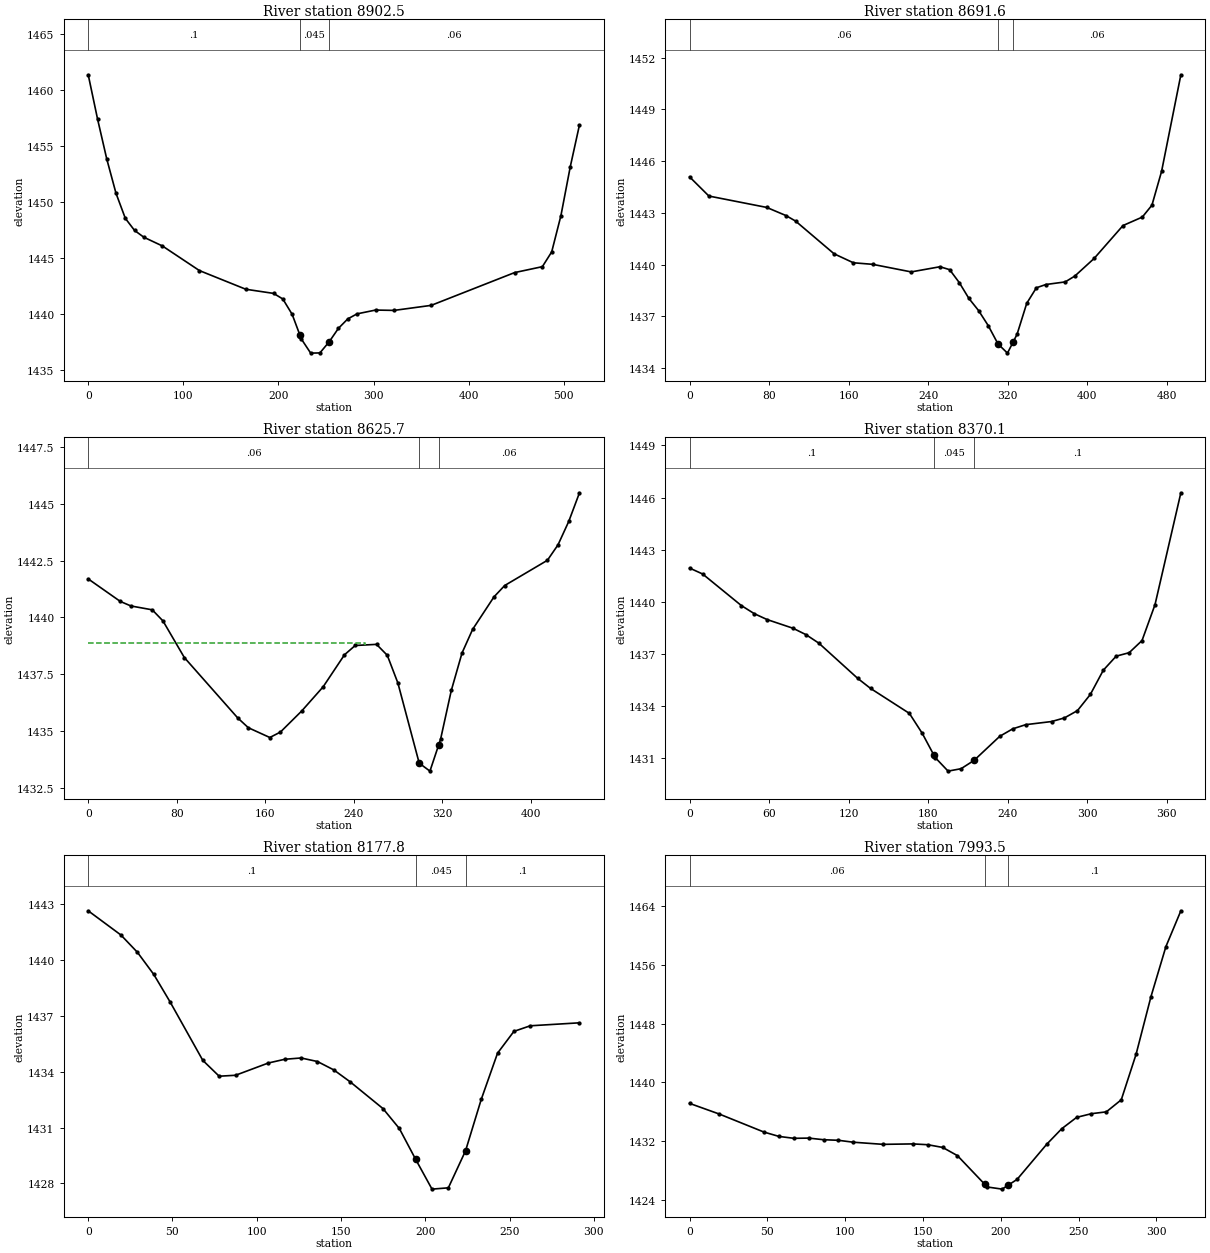
Type RM Length L Ch R = 1 ,8902.5  ,213.9,210.9,207.4
XS GIS Cut Line= 2
     1881423.237      340739.376     1881873.758       340991.98
#Sta/Elev= 30
       0 1461.37     9.8 1457.42    19.5 1453.84    29.2 1450.78      39 1448.54
    48.7 1447.46    58.5 1446.85      78 1446.07   116.9 1443.87   165.7  1442.2
   194.9 1441.83   204.6 1441.33   214.4 1439.96   222.4 1438.14   224.1 1437.75
   233.9 1436.49   243.6 1436.51   253.4 1437.51   263.1 1438.71   272.9 1439.55
   282.6    1440   302.1 1440.34   321.6 1440.31   360.6 1440.76   448.3 1443.69
   477.5 1444.22   487.3 1445.54     497 1448.78   506.8 1453.14   516.5 1456.89
#Mann= 3 , 0 , 0
       0      .1       0   222.4    .045       0   253.4     .06       0
Bank Sta=222.4,253.4
XS Rating Curve= 0 ,0
Exp/Cntr=0.3,0.1

Type RM Length L Ch R = 1 ,8691.6  ,66,65.9,66.2
XS GIS Cut Line= 2
     1881308.183      340946.443     1881772.196       341116.98
#Sta/Elev= 30
       0 1445.09    19.4 1443.98    77.6 1443.32    96.9 1442.85   106.6 1442.53
   145.4 1440.63   164.8 1440.11   184.2 1440.02     223 1439.58     252 1439.88
   261.7 1439.71   271.4 1438.96   281.1 1438.04   290.8 1437.34   300.5 1436.47
   310.4  1435.4   319.9 1434.87   325.4 1435.49   329.6 1435.97   339.3 1437.76
     349 1438.66   358.6 1438.85     378    1439   387.7 1439.34   407.1 1440.36
   436.2 1442.27   455.6 1442.76   465.3 1443.45     475 1445.41   494.4 1451.01
#Mann= 3 , 0 , 0
       0     .06       0   310.4    .045       0   325.4     .06       0
Bank Sta=310.4,325.4
XS Rating Curve= 0 ,0
Exp/Cntr=0.3,0.1

Type RM Length L Ch R = 1 ,8625.7  ,239,255.6,271.4
XS GIS Cut Line= 2
     1881316.864      341014.151     1881733.133      341169.064
#Sta/Elev= 30
       0 1441.69      29  1440.7    38.6  1440.5    57.9 1440.33    67.6 1439.84
    86.9 1438.23   135.2 1435.57   144.8 1435.14   164.2 1434.71   173.8 1434.95
   193.1 1435.88   212.4 1436.94   231.7 1438.35   241.4 1438.76   260.7 1438.81
   270.4 1438.33     280 1437.11   299.3 1433.58     309 1433.23   316.8 1434.37
   318.6 1434.63   328.3 1436.78     338 1438.43   347.6 1439.47   366.9  1440.9
   376.6  1441.4   415.2 1442.51   424.8 1443.19   434.5 1444.22   444.2 1445.48
#Mann= 3 , 0 , 0
       0     .06       0   299.3    .045       0   316.8     .06       0
#XS Ineff= 2 , 0
           250.7 1438.86
Permanent Ineff=
       F       F
Bank Sta=299.3,316.8
XS Rating Curve= 0 ,0
Exp/Cntr=0.3,0.1

Type RM Length L Ch R = 1 ,8370.1  ,194,192.3,190.4
XS GIS Cut Line= 2
      1881306.05      341051.876     1881516.987      341356.564
#Sta/Elev= 30
       0 1441.93     9.8 1441.59      39 1439.77    48.8  1439.3    58.5 1438.96
      78 1438.46    87.8 1438.09    97.5  1437.6   126.8 1435.57   136.5 1434.99
   165.8 1433.55   175.5  1432.4   184.3 1431.14   185.3    1431     195 1430.22
   204.8 1430.36   214.6 1430.84     234 1432.23   243.8 1432.66   253.6  1432.9
   273.1 1433.08   282.8 1433.29   292.6 1433.71   302.3 1434.64   312.1 1436.04
   321.8 1436.85   331.6 1437.05   341.3 1437.75   351.1 1439.82   370.6 1446.27
#Mann= 3 , 0 , 0
       0      .1       0   184.3    .045       0   214.6      .1       0
Bank Sta=184.3,214.6
XS Rating Curve= 0 ,0
Exp/Cntr=0.3,0.1

Type RM Length L Ch R = 1 ,8177.8  ,183,184.3,185.7
XS GIS Cut Line= 2
     1881221.378       341206.86     1881403.669       341434.29
#Sta/Elev= 25
       0 1442.65    19.4 1441.35    29.2 1440.42    38.9 1439.23    48.6 1437.75
      68 1434.61    77.7 1433.76    87.4 1433.81   106.9 1434.47   116.6 1434.67
   126.3 1434.74     136 1434.55   145.7  1434.1   155.4 1433.46   174.9 1432.02
   184.6 1430.95   194.3 1429.29     204 1427.69   213.7 1427.76   223.9 1429.75
   233.2 1432.51   242.9    1435   252.6 1436.17   262.3 1436.47   291.5 1436.63
#Mann= 3 , 0 , 0
       0      .1       0   194.3    .045       0   223.9      .1       0
Bank Sta=194.3,223.9
XS Rating Curve= 0 ,0
Exp/Cntr=0.3,0.1

Type RM Length L Ch R = 1 ,7993.5  ,191.7,192.2,192.8
XS GIS Cut Line= 2
     1881089.904      341317.501     1881272.196      341575.314
#Sta/Elev= 29
       0 1437.14    19.1 1435.69    47.8 1433.24    57.4 1432.65      67 1432.39
    76.6 1432.42    86.1  1432.2    95.7 1432.12   105.2 1431.86   124.4 1431.57
   143.5 1431.63   153.1 1431.52   162.7 1431.15   172.2 1430.03   189.8 1426.12
   191.4 1425.77   200.9 1425.48   204.8 1426.02   210.5  1426.8   229.6 1431.59
   239.2 1433.69   248.8 1435.24   258.3 1435.74   267.9 1435.99   277.5 1437.63
     287 1443.81   296.6 1451.67   306.2 1458.47   315.8 1463.33
#Mann= 3 , 0 , 0
       0     .06       0   189.8    .045       0   204.8      .1       0
Bank Sta=189.8,204.8
XS Rating Curve= 0 ,0
Exp/Cntr=0.3,0.1

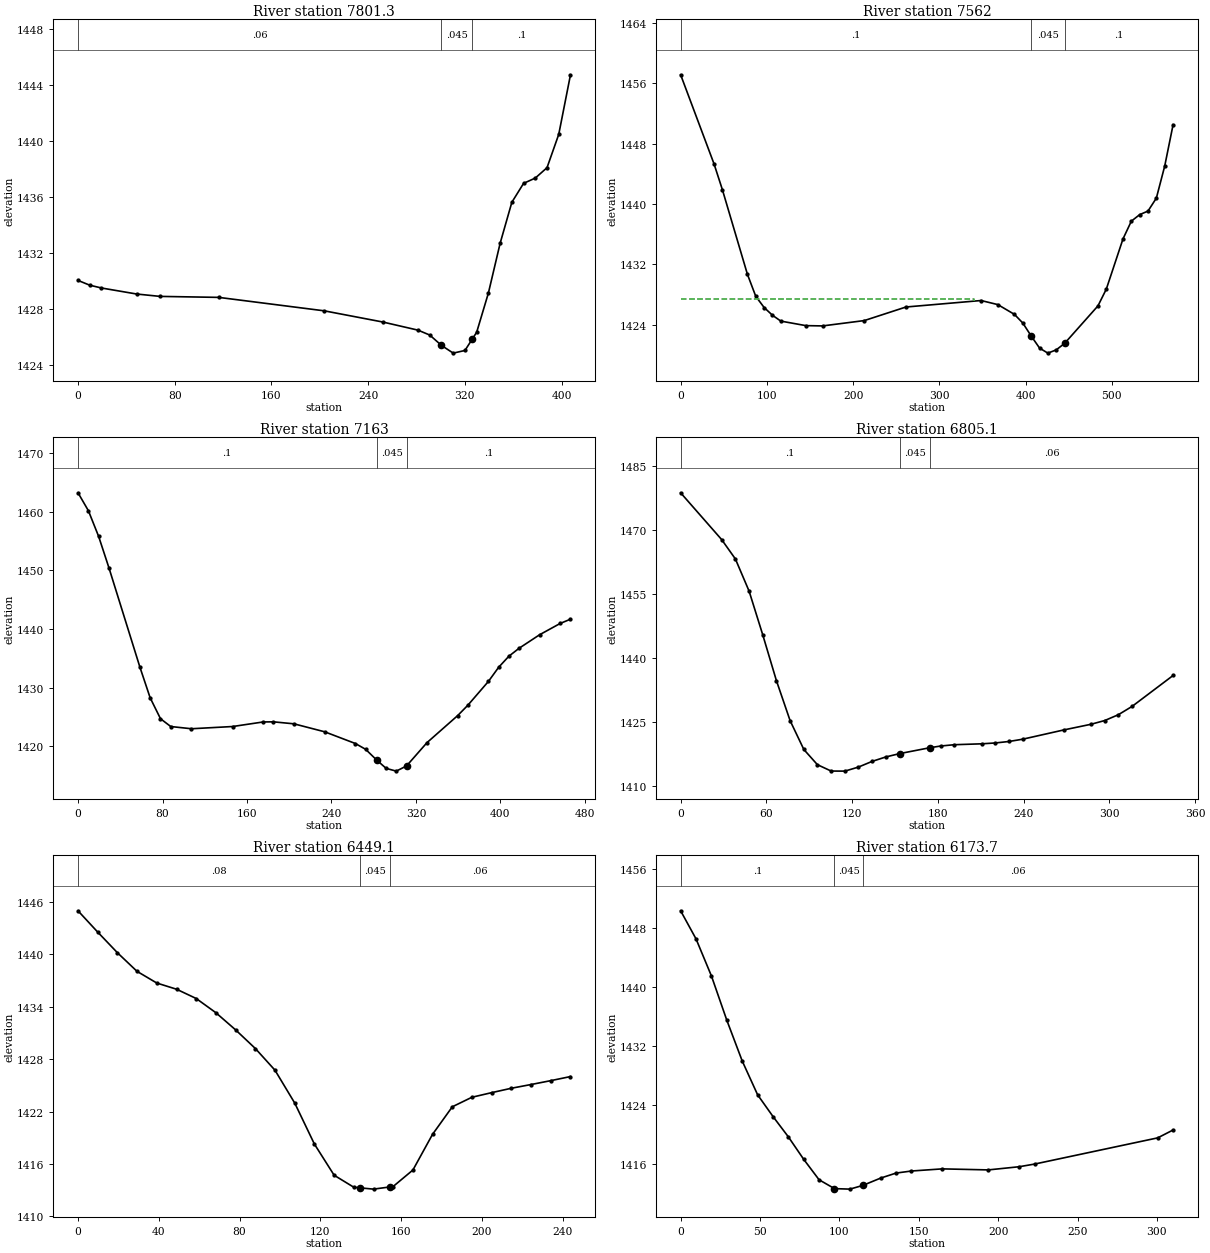
Type RM Length L Ch R = 1 ,7801.3  ,244.1,239.2,234.4
XS GIS Cut Line= 2
     1880884.175      341340.939     1881110.737       341679.48
#Sta/Elev= 23
       0 1430.05     9.7 1429.71    19.4 1429.51    48.5 1429.08    67.9 1428.91
   116.4 1428.84   203.7 1427.88   252.2 1427.08   281.3  1426.5     291 1426.15
   300.7 1425.41   310.4 1424.86   320.1 1425.05   326.2 1425.87   329.8 1426.35
   339.5 1429.15   349.2  1432.7   358.9 1435.63   368.6 1436.98   378.3 1437.36
     388  1438.1   397.7 1440.48   407.4 1444.73
#Mann= 3 , 0 , 0
       0     .06       0   300.7    .045       0   326.2      .1       0
Bank Sta=300.7,326.2
XS Rating Curve= 0 ,0
Exp/Cntr=0.3,0.1

Type RM Length L Ch R = 1 ,7562    ,383.8,399,413.2
XS GIS Cut Line= 2
     1880550.841      341413.855     1880959.225      341812.762
#Sta/Elev= 30
       0 1457.15    38.7 1445.33    48.4  1441.9    77.4 1430.68    87.1 1427.75
    96.8 1426.27   106.4 1425.25   116.1 1424.47   145.1 1423.87   164.5 1423.83
   212.9 1424.54   261.2 1426.34   348.3  1427.2   367.7 1426.66     387 1425.36
   396.7 1424.21   406.4 1422.49   416.1 1420.89   425.7 1420.22   435.4 1420.65
   445.1 1421.51   483.8 1426.49   493.5 1428.72   512.8 1435.37   522.5 1437.73
   532.2  1438.6   541.8 1439.07   551.5 1440.79   561.2 1445.05   570.9 1450.53
#Mann= 3 , 0 , 0
       0      .1       0   406.4    .045       0   445.1      .1       0
#XS Ineff= 2 , 0
          339.72 1427.39
Permanent Ineff=
       F       F
Bank Sta=406.4,445.1
XS Rating Curve= 0 ,0
Exp/Cntr=0.3,0.1

Type RM Length L Ch R = 1 ,7163    ,377.8,357.9,337.6
XS GIS Cut Line= 4
     1880394.591      341682.085     1880511.779      341752.397
     1880571.675      341997.189     1880631.571      342046.668
#Sta/Elev= 30
       0 1463.23     9.8 1460.18    19.5  1455.8    29.3 1450.42    58.6 1433.49
    68.3 1428.26    78.1 1424.69    87.8 1423.36   107.4 1422.98   146.4 1423.36
   175.4 1424.14   185.1 1424.16   204.5 1423.82   233.6 1422.46   262.7 1420.46
   272.4 1419.47   282.7 1417.67   291.8 1416.22   301.4 1415.75   311.1 1416.63
   330.5 1420.61   359.6 1425.23   369.3 1427.01   388.7 1431.06   398.4 1433.47
   408.1 1435.36   417.8 1436.72   437.2 1439.02   456.6 1440.94   466.4 1441.67
#Mann= 3 , 0 , 0
       0      .1       0   282.7    .045       0   311.1      .1       0
Bank Sta=282.7,311.1
XS Rating Curve= 0 ,0
Exp/Cntr=0.3,0.1

Type RM Length L Ch R = 1 ,6805.1  ,359.3,356,352.7
XS GIS Cut Line= 2
     1880173.237      342057.085     1880485.267      342203.387
#Sta/Elev= 28
       0 1478.79    28.7 1467.81    38.3 1463.27    47.9 1455.71    57.4 1445.51
      67 1434.72    76.6 1425.31    86.2 1418.55    95.7 1414.98   105.3 1413.49
   114.9 1413.47   124.4 1414.42     134 1415.76   143.6  1416.8   153.2 1417.58
   174.3 1418.96   181.9 1419.36   191.5 1419.67   210.6 1419.88   220.2 1420.08
   229.8 1420.43   239.3 1420.96     268 1423.13   287.2 1424.47   296.8 1425.35
   306.3 1426.71   315.9 1428.66   344.6 1435.92
#Mann= 3 , 0 , 0
       0      .1       0   153.2    .045       0   174.3     .06       0
Bank Sta=153.2,174.3
XS Rating Curve= 0 ,0
Exp/Cntr=0.3,0.1

Type RM Length L Ch R = 1 ,6449.1  ,266,275.4,284.9
XS GIS Cut Line= 2
     1880053.446      342408.647     1880285.216      342484.168
#Sta/Elev= 28
       0 1444.99     9.8 1442.54    19.5 1440.19    29.2 1438.06      39 1436.72
    48.8 1436.01    58.5 1434.95    68.2 1433.33      78 1431.36    87.8 1429.22
    97.5 1426.74   107.3 1422.97     117 1418.29   126.8 1414.71   136.5 1413.34
   139.4 1413.27   146.3 1413.12   154.4 1413.37     156 1413.42   165.8 1415.31
   175.5 1419.39   185.3 1422.55     195 1423.64   204.8 1424.17   214.5 1424.67
   224.3  1425.1     234 1425.54   243.8 1426.01
#Mann= 3 , 0 , 0
       0     .08       0   139.4    .045       0   154.4     .06       0
Bank Sta=139.4,154.4
XS Rating Curve= 0 ,0
Exp/Cntr=0.3,0.1

Type RM Length L Ch R = 1 ,6173.7  ,148.8,146.5,144.2
XS GIS Cut Line= 2
     1879915.425      342567.501       1880149.8      342770.626
#Sta/Elev= 22
       0 1450.32     9.7  1446.5    19.4 1441.47    29.1 1435.45    38.8 1429.92
    48.5 1425.33    58.2 1422.38    67.8 1419.64    77.5 1416.58    87.2  1413.8
    96.9  1412.6   106.6 1412.53   114.7 1413.03     126 1414.03   135.7 1414.71
   145.4 1414.99   164.8 1415.28   193.8 1415.14   213.2 1415.57   222.9 1415.93
   300.5 1419.49   310.2 1420.56
#Mann= 3 , 0 , 0
       0      .1       0    96.9    .045       0   114.7     .06       0
Bank Sta=96.9,114.7
XS Rating Curve= 0 ,0
Exp/Cntr=0.3,0.1

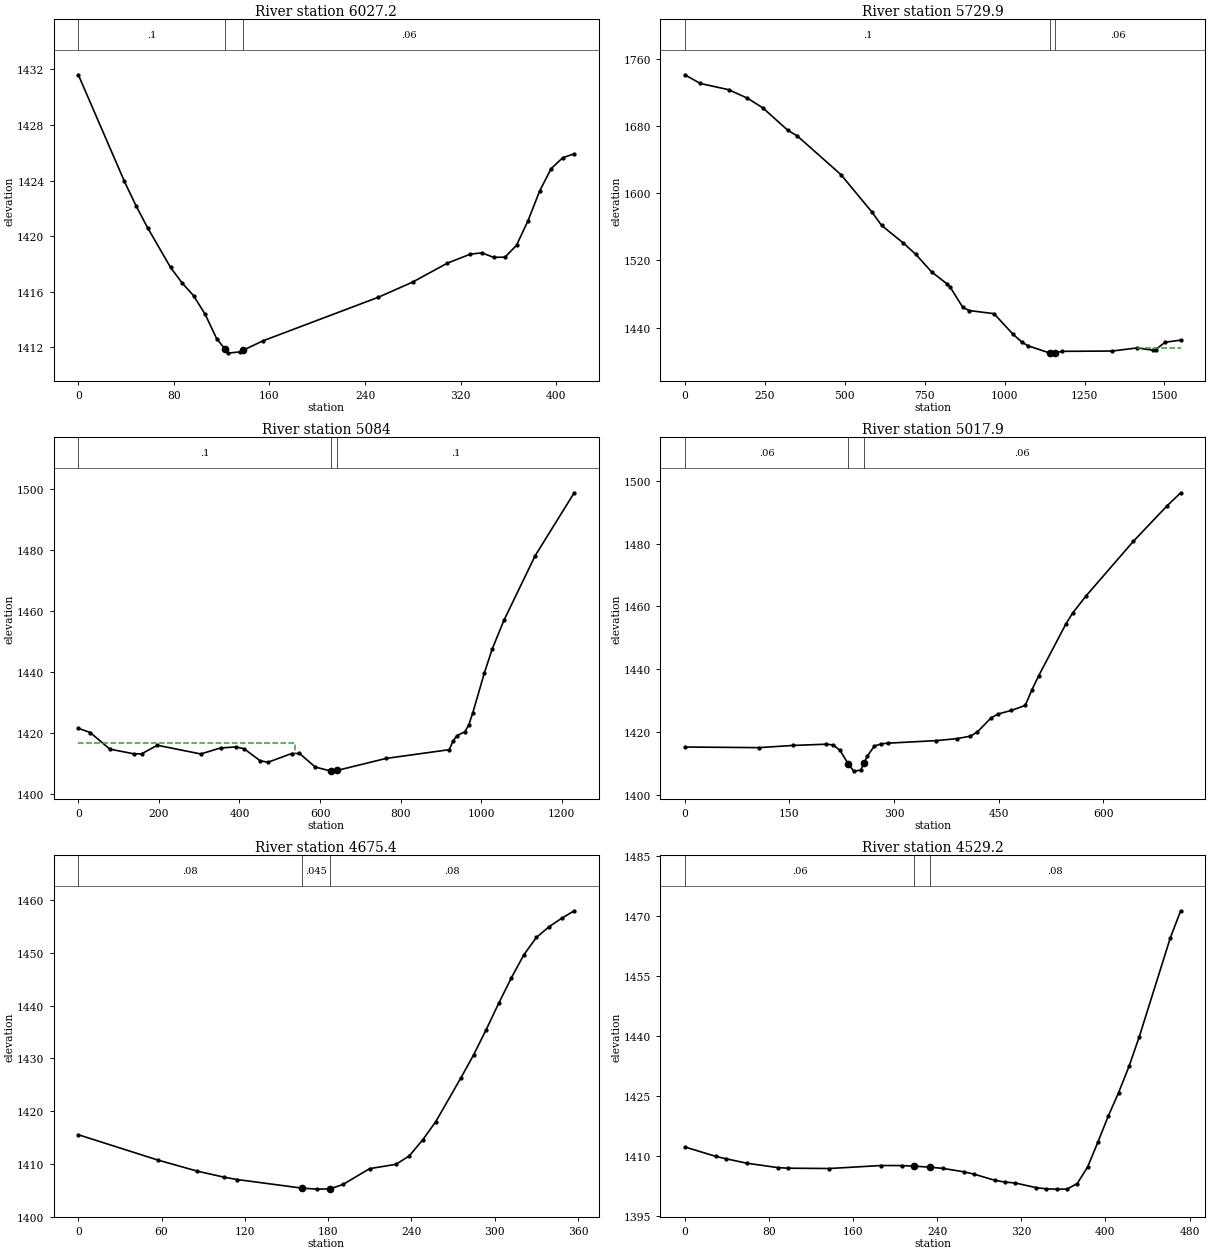
Type RM Length L Ch R = 1 ,6027.2  ,311,297.3,282.7
XS GIS Cut Line= 2
     1879794.765      342671.668     1880134.572      342909.985
#Sta/Elev= 27
       0 1431.61    38.6 1423.93    48.3 1422.18    57.9 1420.61    77.2 1417.74
    86.9 1416.62    96.5  1415.7   106.2 1414.36   115.8 1412.61     123 1411.84
   125.5 1411.57   135.1 1411.66     138 1411.78   154.4 1412.45     251 1415.59
   279.9 1416.69   308.9 1418.05   328.2  1418.7   337.8 1418.79   347.5 1418.47
   357.1 1418.48   366.8 1419.34   376.4 1421.11   386.1 1423.24   395.7 1424.85
   405.4 1425.64     415 1425.92
#Mann= 3 , 0 , 0
       0      .1       0     123    .045       0     138     .06       0
Bank Sta=123,138
XS Rating Curve= 0 ,0
Exp/Cntr=0.3,0.1

Type RM Length L Ch R = 1 ,5729.9  ,676,645.9,614.3
XS GIS Cut Line= 3
     1878602.454      342937.328     1879616.343      342999.828
     1880151.065      343006.773
#Sta/Elev= 30
       0  1741.1    48.8 1730.78   136.7 1723.43   195.4  1713.4   244.2 1701.68
   322.3    1675   351.6  1668.4   488.4 1622.21     586 1577.34   615.4 1561.74
   683.7 1540.71   722.8  1527.2   771.6 1506.51   820.5 1492.02   830.2 1488.17
   869.3 1464.28   888.8 1460.43     967 1456.68  1025.5 1432.58  1054.7 1422.56
  1074.2 1418.35    1142 1409.69    1157 1410.27  1181.1 1411.81  1336.7  1412.2
  1414.5 1415.88  1463.1 1413.27  1472.8 1413.97    1502 1422.63  1550.6 1425.16
#Mann= 3 , 0 , 0
       0      .1       0    1142    .045       0    1157     .06       0
#XS Ineff= 2 , 0
                         1415.25         1416.08
Permanent Ineff=
       F       F
Bank Sta=1142,1157
XS Rating Curve= 0 ,0
Exp/Cntr=0.3,0.1

Type RM Length L Ch R = 1 ,5084    ,69,66.1,64.7
XS GIS Cut Line= 4
     1880056.447      344047.137     1880011.779       343460.73
     1880078.318      343134.982     1880387.714      343115.624
#Sta/Elev= 30
       0 1421.45    29.4 1420.08    78.4 1414.62   137.2 1413.11   156.8 1413.07
     196  1415.9   303.8 1413.05   352.9 1415.01   392.1 1415.35   411.7 1414.73
   450.9 1410.85   470.5 1410.32   529.3 1413.18   548.9 1413.21   588.1 1408.76
   627.2 1407.42   628.1 1407.43   643.1 1407.68   764.1 1411.59   920.6 1414.45
   930.3 1417.38     940 1419.08   959.3  1420.3     969 1422.55   978.7  1426.4
  1007.8 1439.63  1027.1  1447.4  1056.2 1456.82  1133.7    1478  1230.6 1498.64
#Mann= 3 , 0 , 0
       0      .1       0   628.1    .045       0   643.1      .1       0
#XS Ineff= 2 , 0
          538.31 1416.53
Permanent Ineff=
       F       F
Bank Sta=628.1,643.1
XS Rating Curve= 0 ,0
Exp/Cntr=0.3,0.1

Type RM Length L Ch R = 1 ,5017.9  ,322.3,342.5,362.8
XS GIS Cut Line= 4
     1880089.904      343653.439     1880076.883       343460.73
     1880132.215      343170.792     1880354.728       343157.29
#Sta/Elev= 30
       0 1415.25   106.2 1415.05   154.5 1415.74     203 1416.15   212.8  1415.9
   222.7 1414.17   234.5 1409.86   242.3 1407.57   252.2 1407.88   256.91410.067
     262 1412.44   271.9 1415.55   281.7 1416.25   291.5 1416.48   360.4 1417.28
   389.9 1417.91   409.6  1418.7   419.4 1419.99   439.1 1424.48     449 1425.73
   468.6 1426.92   488.3 1428.49     498  1433.5   507.7 1437.99   546.5 1454.37
   556.2 1457.88   575.6 1463.38   643.4 1480.76   691.9 1492.09   711.2  1496.2
#Mann= 3 , 0 , 0
       0     .06       0   234.5    .045       0   256.9     .06       0
Bank Sta=234.5,256.9
XS Rating Curve= 0 ,0
Exp/Cntr=0.3,0.1

Type RM Length L Ch R = 1 ,4675.4  ,155.7,146.2,136.7
XS GIS Cut Line= 3
     1880102.925      343765.418     1880329.487      343643.022
     1880384.175      343559.689
#Sta/Elev= 24
       0 1415.52    57.2 1410.73    85.8 1408.61   104.9 1407.48   114.4 1407.03
   161.1  1405.4   171.7 1405.21   181.2 1405.25   190.8 1406.11   209.8 1409.09
   228.9 1409.92   238.4  1411.5     248 1414.52   257.5    1418   275.6  1426.3
   284.7 1430.62   293.8 1435.43   302.8 1440.41   311.9 1445.23   320.9 1449.61
     330 1452.91   339.1 1454.94   348.1 1456.53   357.2 1457.96
#Mann= 3 , 0 , 0
       0     .08       0   161.1    .045       0   181.2     .08       0
Bank Sta=161.1,181.2
XS Rating Curve= 0 ,0
Exp/Cntr=0.3,0.1

Type RM Length L Ch R = 1 ,4529.2  ,287.1,301.3,315.5
XS GIS Cut Line= 2
     1880178.446       343978.96     1880480.529       343616.98
#Sta/Elev= 30
       0 1412.34    29.5 1409.98    39.3 1409.38    58.9 1408.28    88.4 1407.18
    98.2 1407.03   137.5 1406.95   186.6  1407.7   206.3 1407.68     218 1407.54
     233 1407.29   245.6 1406.97   265.2 1406.13     275 1405.55   294.7 1404.01
   304.5 1403.56   314.3 1403.33     334 1402.18   343.8 1401.86   353.6  1401.8
   363.4 1401.81   373.2 1403.19   383.1 1407.36   392.9 1413.59   402.7 1420.06
   412.5 1425.89   422.4 1432.46   432.2 1439.89   461.6  1464.5   471.5 1471.33
#Mann= 3 , 0 , 0
       0     .06       0     218    .045       0     233     .08       0
Bank Sta=218,233
XS Rating Curve= 0 ,0
Exp/Cntr=0.3,0.1