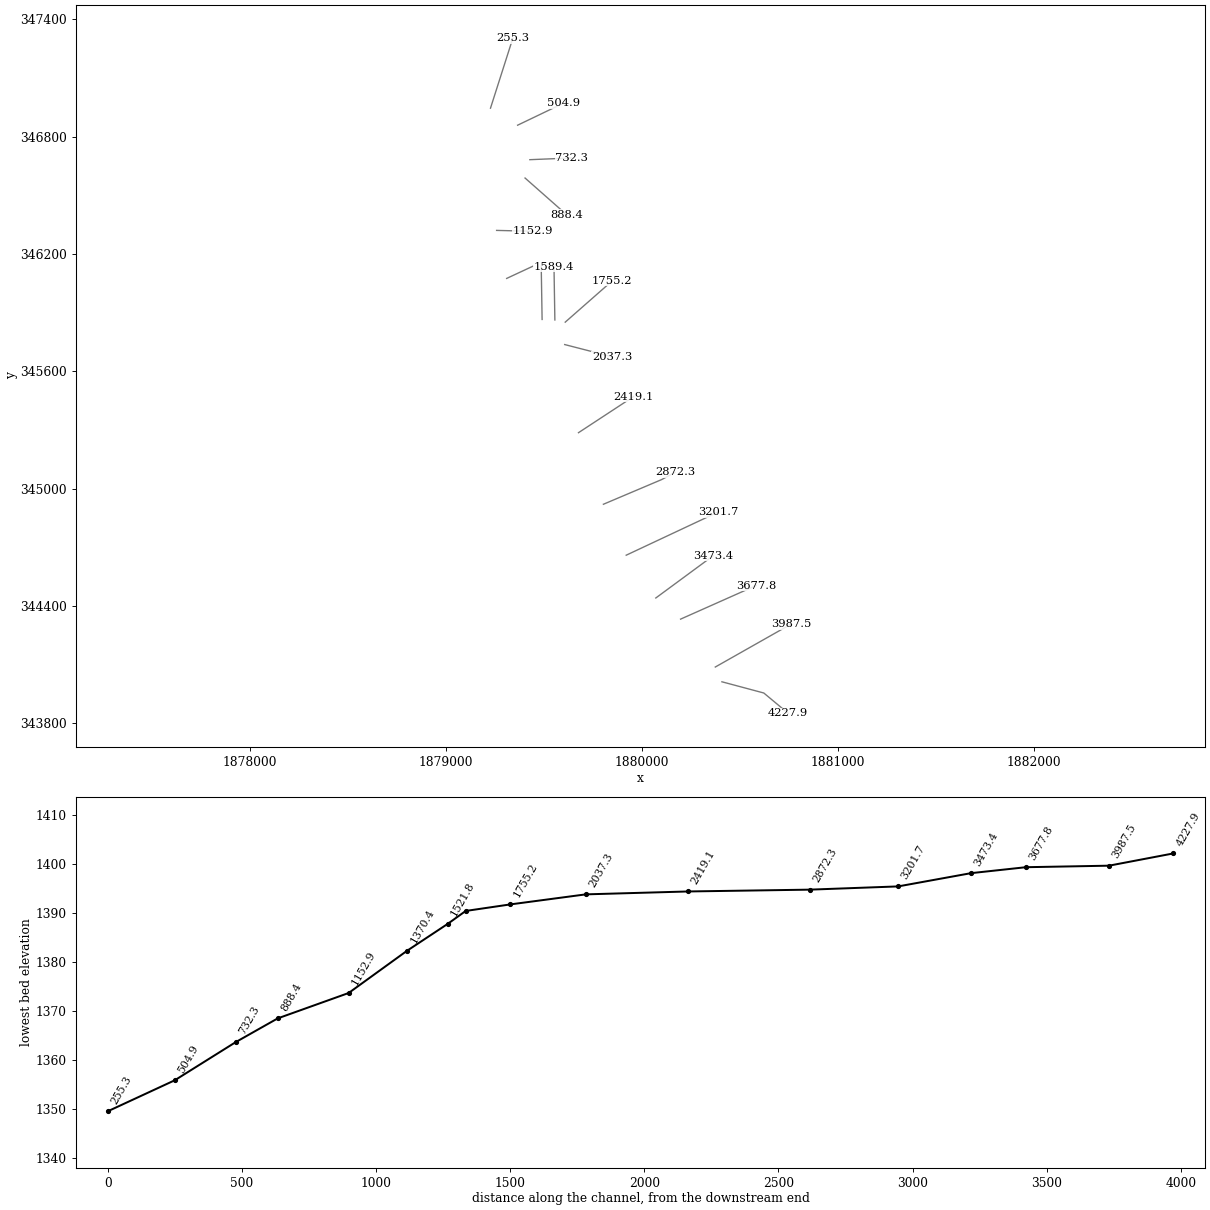
HEC-RAS study BIRDSCK.prj: BIRDSCK

--- BIRDSCK.g01 (geometry) --- (continued)

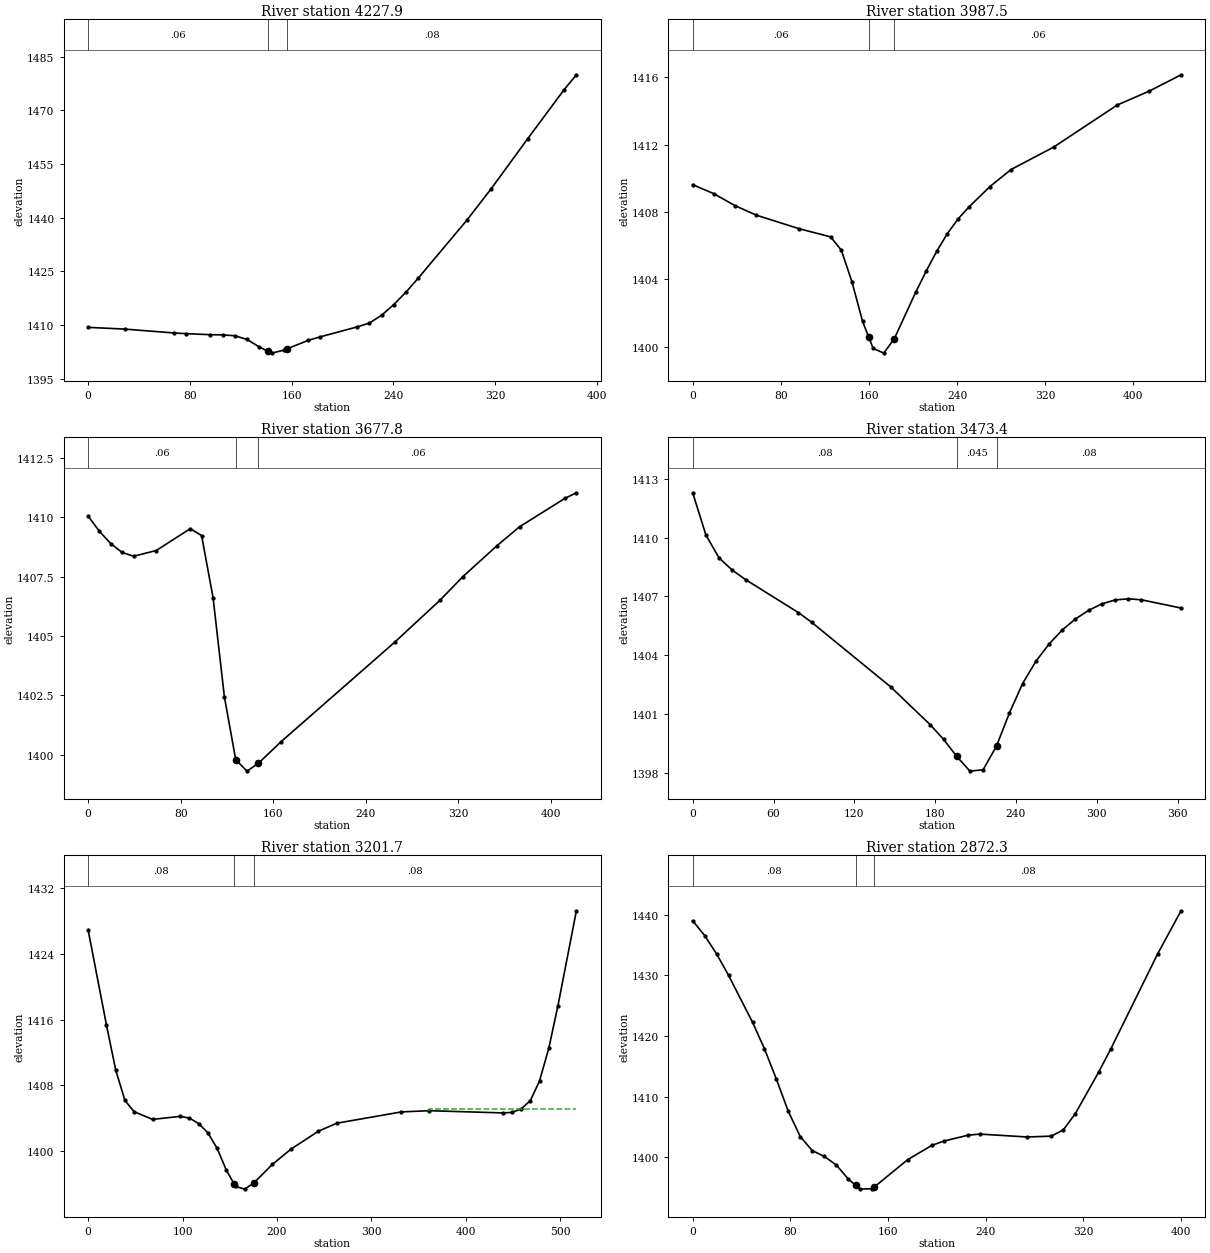
Type RM Length L Ch R = 1 ,4227.9  ,222,240.4,258.9
XS GIS Cut Line= 3
     1880407.612      344012.814     1880621.154      343955.522
     1880746.154      343851.355
#Sta/Elev= 26
       0 1409.32    28.8 1408.84    67.3 1407.76    76.9 1407.56    96.1 1407.27
   105.7 1407.22   115.4 1406.97     125 1405.93   134.6 1403.84   141.6 1402.59
   144.2 1402.12   153.8 1402.94   156.6 1403.35     173 1405.68   182.6 1406.68
   211.5 1409.45   221.1 1410.52   230.7  1412.7   240.2 1415.67   249.8 1419.14
   259.4 1423.03   297.7 1439.26   316.8 1448.04   345.5 1462.02   374.2 1475.76
   383.8 1479.89
#Mann= 3 , 0 , 0
       0     .06       0   141.6    .045       0   156.6     .08       0
Bank Sta=141.6,156.6
XS Rating Curve= 0 ,0
Exp/Cntr=0.3,0.1

Type RM Length L Ch R = 1 ,3987.5  ,311.3,309.7,308.1
XS GIS Cut Line= 2
     1880373.758      344088.335     1880759.175      344307.085
#Sta/Elev= 25
       0 1409.62    19.3 1409.08    38.5 1408.37    57.8 1407.81    96.3 1407.01
   125.2 1406.52   134.9 1405.73   144.5 1403.86   154.2  1401.5   159.7 1400.58
   163.8  1399.9   173.4 1399.62     183 1400.48   202.3 1403.22     212  1404.5
   221.6 1405.68   231.2 1406.72   240.8 1407.58   250.5 1408.28   269.8 1409.51
     289 1410.52   327.6 1411.85   385.4 1414.35   414.3 1415.17   443.2 1416.14
#Mann= 3 , 0 , 0
       0     .06       0   159.7    .045       0     183     .06       0
Bank Sta=159.7,183
XS Rating Curve= 0 ,0
Exp/Cntr=0.3,0.1

Type RM Length L Ch R = 1 ,3677.8  ,200.7,204.4,208.1
XS GIS Cut Line= 2
     1880196.675      344333.126     1880582.091      344505.001
#Sta/Elev= 21
       0 1410.05     9.8 1409.41    19.6 1408.89    29.4 1408.52    39.3 1408.36
    58.9  1408.6    88.3 1409.52    98.1 1409.23     108 1406.62   117.8 1402.44
   127.6 1399.79   137.4 1399.31   147.2 1399.64   166.8 1400.55     265 1404.74
   304.2 1406.51   323.9  1407.5   353.3  1408.8   372.9  1409.6   412.2  1410.8
     422 1411.03
#Mann= 3 , 0 , 0
       0     .06       0   127.6    .045       0   147.2     .06       0
Bank Sta=127.6,147.2
XS Rating Curve= 0 ,0
Exp/Cntr=0.3,0.1

Type RM Length L Ch R = 1 ,3473.4  ,275.7,271.8,267.8
XS GIS Cut Line= 2
     1880070.336      344441.235     1880362.003      344656.512
#Sta/Elev= 26
       0 1412.28     9.8 1410.13    19.6 1408.96    29.4 1408.34    39.2 1407.86
    78.4 1406.18    88.2 1405.69     147 1402.39   176.4 1400.46   186.2 1399.72
     196 1398.85   205.8  1398.1   215.6 1398.17   225.6 1399.39   235.1 1401.06
   244.9 1402.56   254.7 1403.69   264.5 1404.57   274.3 1405.29   284.1 1405.85
   293.9 1406.29   303.7 1406.62   313.5 1406.82   323.3 1406.88   333.1 1406.83
   362.5 1406.41
#Mann= 3 , 0 , 0
       0     .08       0     196    .045       0   225.6     .08       0
Bank Sta=196,225.6
XS Rating Curve= 0 ,0
Exp/Cntr=0.3,0.1

Type RM Length L Ch R = 1 ,3201.7  ,330.6,329.4,328.2
XS GIS Cut Line= 2
     1879919.294      344659.985     1880387.176      344880.037
#Sta/Elev= 30
       0 1426.91    19.5 1415.32    29.3 1409.85      39 1406.18    48.8  1404.8
    68.3 1403.87    97.6 1404.24   107.3 1404.03   117.1 1403.36   126.8 1402.25
   136.6 1400.36   146.3 1397.73   154.4 1396.08   156.1 1395.73   165.8  1395.4
   175.6 1396.16   195.1  1398.4   214.6 1400.24   243.9 1402.44   263.4 1403.41
   331.7 1404.78     361 1404.93     439 1404.66   448.8 1404.72   458.5 1405.14
   468.3 1406.16     478 1408.55   487.8 1412.51   497.5 1417.69     517 1429.21
#Mann= 3 , 0 , 0
       0     .08       0   154.4    .045       0   175.6     .08       0
#XS Ineff= 2 , 0
                          360.85         1405.14
Permanent Ineff=
       F       F
Bank Sta=154.4,175.6
XS Rating Curve= 0 ,0
Exp/Cntr=0.3,0.1

Type RM Length L Ch R = 1 ,2872.3  ,449,453.1,457.1
XS GIS Cut Line= 3
     1879802.975      344920.401     1880100.321      345046.668
     1880168.029      345083.126
#Sta/Elev= 30
       0 1438.99     9.8 1436.56    19.6 1433.52    29.4 1429.98      49 1422.26
    58.7 1417.92    68.5 1412.89    78.3 1407.56    88.1  1403.4    97.9  1401.1
   107.7 1400.14   117.5 1398.74   127.3 1396.44   133.5 1395.35     137 1394.74
   146.8 1394.81   148.5 1395.06   176.2 1399.62   195.8 1401.95   205.6 1402.66
   225.2 1403.62   234.9 1403.82   274.1 1403.34   293.7 1403.48   303.5 1404.51
   313.3 1407.17   332.7 1414.12   342.3 1417.82   380.7 1433.51   399.9 1440.64
#Mann= 3 , 0 , 0
       0     .08       0   133.5    .045       0   148.5     .08       0
Bank Sta=133.5,148.5
XS Rating Curve= 0 ,0
Exp/Cntr=0.3,0.1

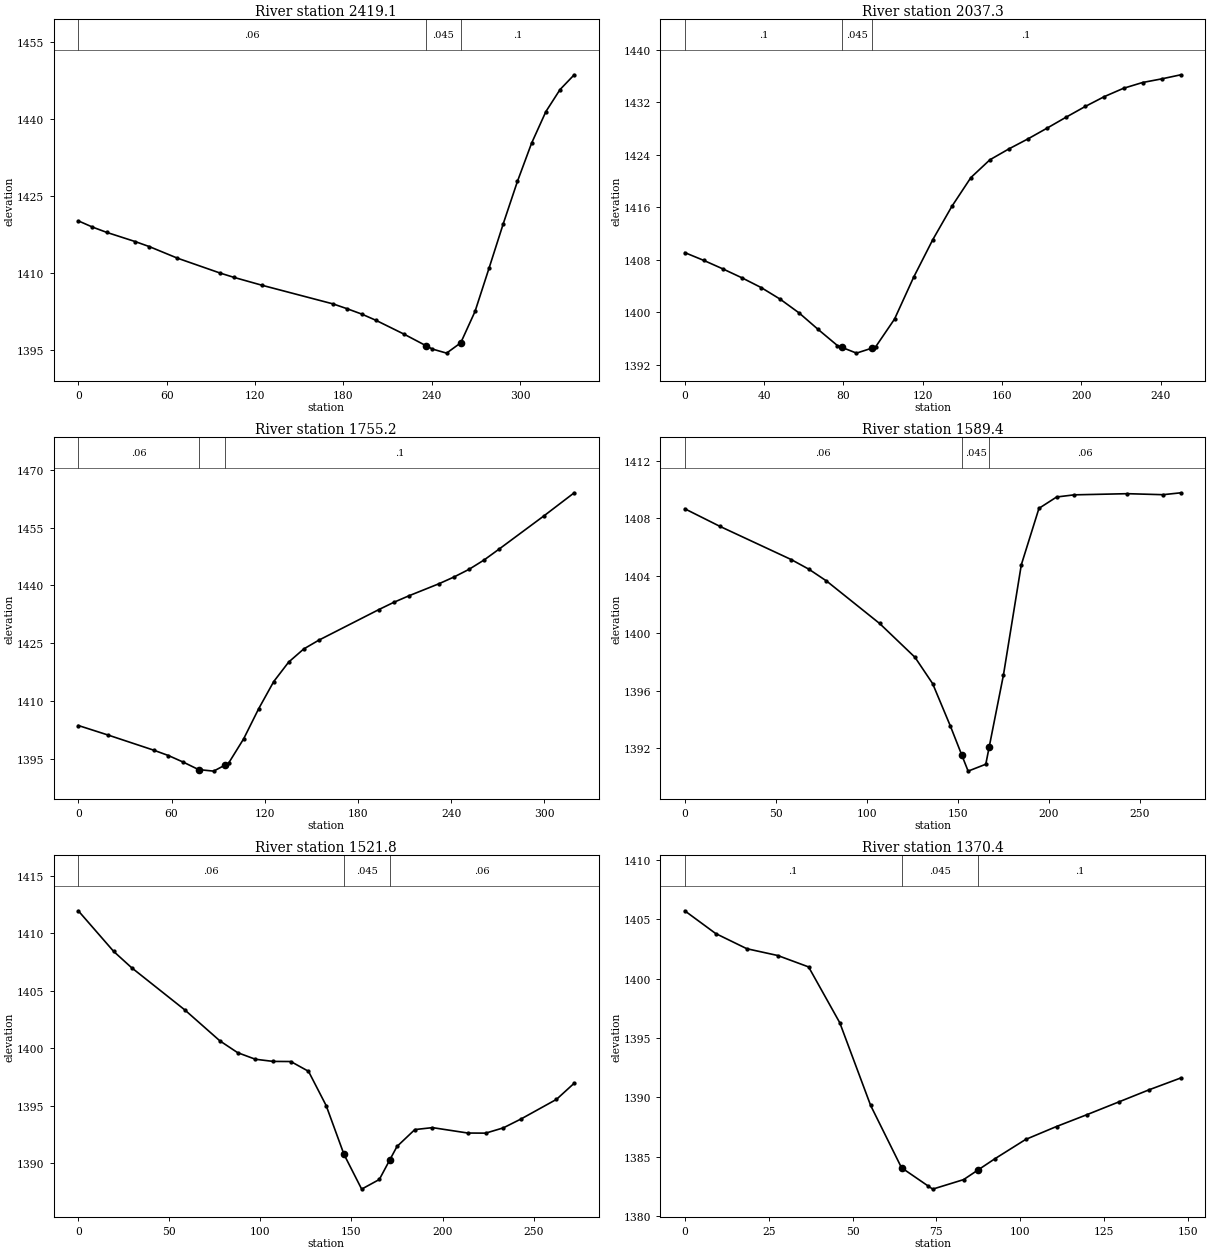
Type RM Length L Ch R = 1 ,2419.1  ,401.5,381.8,362.9
XS GIS Cut Line= 2
     1879675.841      345286.251     1879957.091      345471.147
#Sta/Elev= 26
       0 1420.18     9.6 1418.97    19.2 1417.94    38.5 1416.15    48.1 1415.17
    67.3  1412.9    96.2    1410   105.8 1409.14     125 1407.59   173.1 1403.96
   182.7 1403.01   192.3    1402     202 1400.78   221.2 1398.06   235.8 1395.85
   240.4 1395.16     250 1394.37   259.6 1396.38   269.3  1402.5   278.9 1411.02
   288.5 1419.65   298.1 1427.89   307.7 1435.34   317.4  1441.5     327  1445.8
   336.6 1448.68
#Mann= 3 , 0 , 0
       0     .06       0   235.8    .045       0   259.6      .1       0
Bank Sta=235.8,259.6
XS Rating Curve= 0 ,0
Exp/Cntr=0.3,0.1

Type RM Length L Ch R = 1 ,2037.3  ,259.2,282.1,304.1
XS GIS Cut Line= 2
     1879605.529      345736.772     1879847.716      345674.272
#Sta/Elev= 29
       0 1409.09     9.6  1407.9    19.2 1406.61    28.9 1405.24    38.5 1403.77
    48.1    1402    57.7 1399.89    67.3 1397.38      77 1394.93    79.3 1394.65
    86.6 1393.78    94.3 1394.53    96.2 1394.71   105.8 1398.97   115.4 1405.32
   125.1 1411.07   134.7 1416.13   144.3 1420.52   153.9 1423.23   163.5 1424.89
   173.2 1426.43   182.8 1428.06   192.4 1429.73     202 1431.35   211.6 1432.85
   221.3 1434.12   230.9    1435   240.5 1435.55   250.1 1436.17
#Mann= 3 , 0 , 0
       0      .1       0    79.3    .045       0    94.3      .1       0
Bank Sta=79.3,94.3
XS Rating Curve= 0 ,0
Exp/Cntr=0.3,0.1

Type RM Length L Ch R = 1 ,1755.2  ,142.5,165.9,188.6
XS GIS Cut Line= 2
     1879608.133      345851.355     1879847.716      346062.293
#Sta/Elev= 25
       0 1403.58    19.4 1401.07    48.4 1397.19      58 1395.78    67.7 1394.04
    77.4 1392.13    87.1 1391.73    94.7 1393.35    96.7 1393.78   106.4  1400.1
   116.1 1407.94   125.8    1415   135.4 1420.05   145.1 1423.46   154.8 1425.74
   193.5  1433.7   203.1 1435.58   212.8 1437.27   232.2 1440.41   241.8 1442.15
   251.5 1444.14   261.2 1446.57   270.8 1449.38   299.9 1458.08   319.2 1464.02
#Mann= 3 , 0 , 0
       0     .06       0    77.4    .045       0    94.7      .1       0
Bank Sta=77.4,94.7
XS Rating Curve= 0 ,0
Exp/Cntr=0.3,0.1

Type RM Length L Ch R = 1 ,1589.4  ,70.7,67.6,65.1
XS GIS Cut Line= 2
     1879555.313      345862.543      1879550.85       346134.79
#Sta/Elev= 21
       0 1408.65    19.4 1407.42    58.4 1405.12    68.1 1404.45    77.8 1403.63
     107 1400.67   126.4 1398.32   136.1 1396.49   145.9 1393.52   152.2 1391.49
   155.6  1390.4   165.3 1390.88   167.2  1392.1     175 1397.09   184.8 1404.75
   194.5 1408.68   204.2 1409.47   213.9 1409.62   243.1  1409.7   262.6 1409.63
   272.3 1409.76
#Mann= 3 , 0 , 0
       0     .06       0   152.2    .045       0   167.2     .06       0
Bank Sta=152.2,167.2
XS Rating Curve= 0 ,0
Exp/Cntr=0.3,0.1

Type RM Length L Ch R = 1 ,1521.8  ,178.7,151.4,124
XS GIS Cut Line= 2
     1879490.209      345865.147     1879485.746      346137.394
#Sta/Elev= 24
       0 1411.96    19.4 1408.43    29.2 1407.02    58.4 1403.35    77.8 1400.64
    87.5 1399.62    97.2 1399.05     107 1398.86   116.7 1398.85   126.4    1398
   136.1 1395.02   145.9 1390.77   155.6 1387.75   165.3 1388.59     171 1390.28
     175 1391.46   184.8 1392.93   194.5  1393.1   213.9 1392.63   223.7 1392.62
   233.4 1393.08   243.1 1393.85   262.6 1395.56   272.3 1396.96
#Mann= 3 , 0 , 0
       0     .06       0   145.9    .045       0     171     .06       0
Bank Sta=145.9,171
XS Rating Curve= 0 ,0
Exp/Cntr=0.3,0.1

Type RM Length L Ch R = 1 ,1370.4  ,227.9,217.4,207
XS GIS Cut Line= 2
     1879309.455      346074.911     1879443.347      346137.394
#Sta/Elev= 19
       0  1405.7     9.2 1403.79    18.5 1402.51    27.7 1401.94    36.9 1400.98
    46.2 1396.28    55.4 1389.32    64.6 1384.08    72.4 1382.57    73.9 1382.28
    83.1 1383.08    87.4 1383.89    92.4 1384.83   101.6 1386.46   110.8 1387.55
     120 1388.56   129.3 1389.61   138.5 1390.65   147.8 1391.63
#Mann= 3 , 0 , 0
       0      .1       0    64.6    .045       0    87.4      .1       0
Bank Sta=64.6,87.4
XS Rating Curve= 0 ,0
Exp/Cntr=0.3,0.1

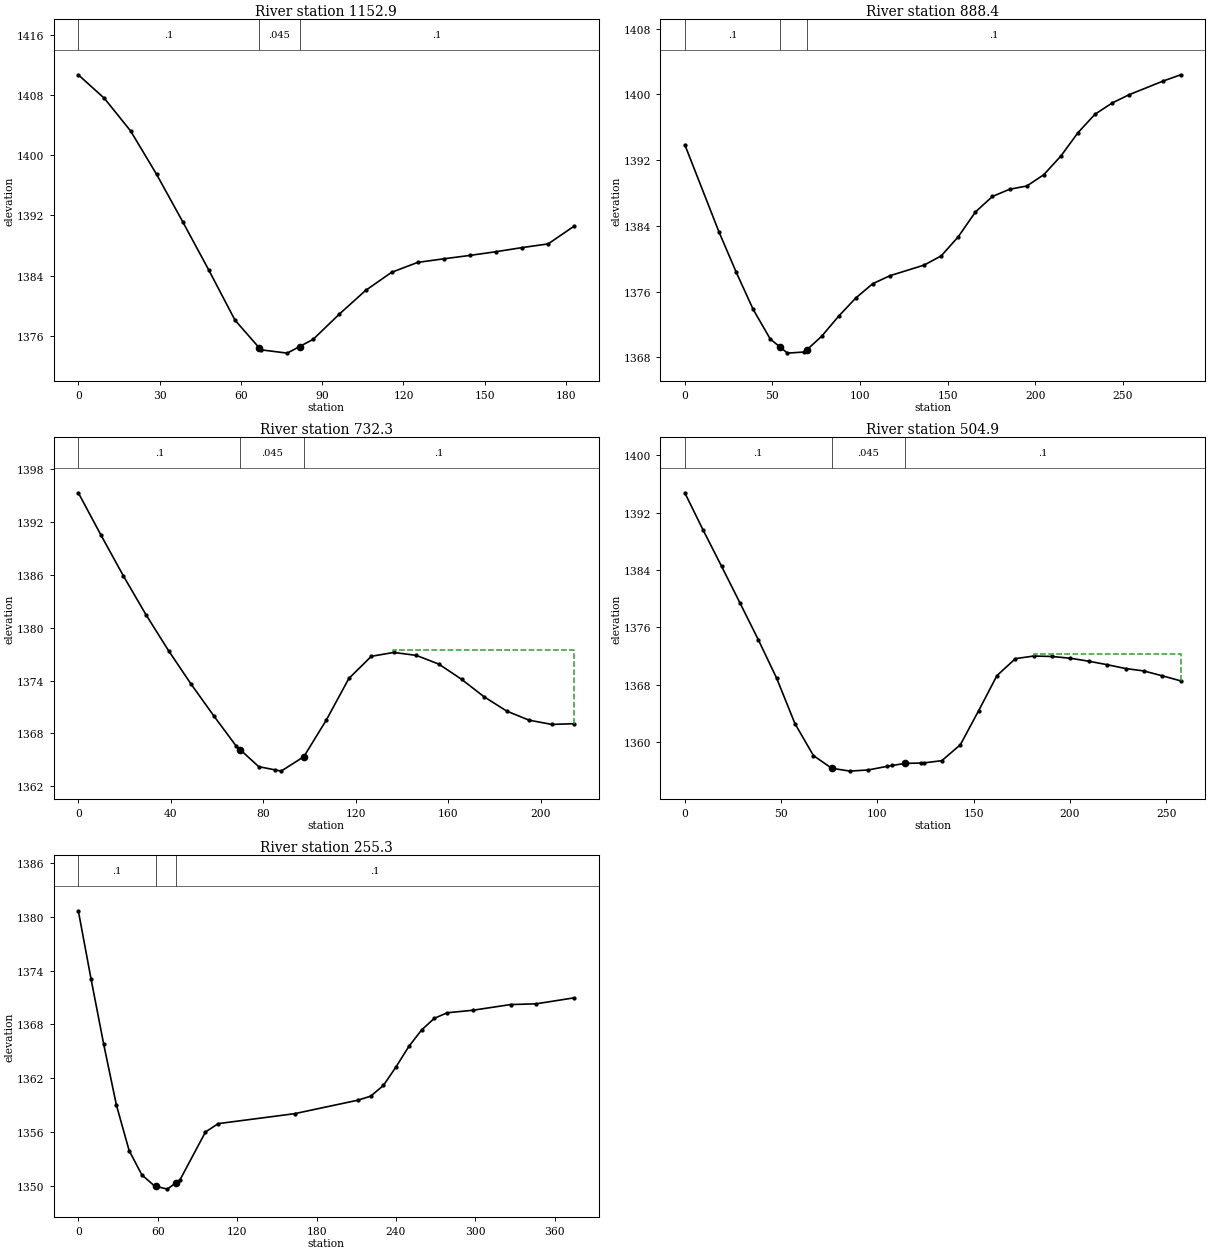
Type RM Length L Ch R = 1 ,1152.9  ,280.5,264.5,248.6
XS GIS Cut Line= 2
      1879258.13      346320.379     1879441.115      346315.916
#Sta/Elev= 22
       0 1410.66     9.6 1407.54    19.3  1403.2    28.9 1397.43    38.5 1391.16
    48.2 1384.69    57.8 1378.08    66.7 1374.42    67.4 1374.13    77.1 1373.69
    81.7 1374.57    86.7 1375.53    96.3 1378.86     106 1382.01   115.6 1384.42
   125.2 1385.74   134.9 1386.22   144.5 1386.67   154.1 1387.16   163.8 1387.71
   173.4  1388.2     183 1390.56
#Mann= 3 , 0 , 0
       0      .1       0    66.7    .045       0    81.7      .1       0
Bank Sta=66.7,81.7
XS Rating Curve= 0 ,0
Exp/Cntr=0.3,0.1

Type RM Length L Ch R = 1 ,888.4   ,138.3,156.1,173.8
XS GIS Cut Line= 2
     1879403.179      346588.163     1879615.175      346400.715
#Sta/Elev= 29
       0 1393.88    19.5 1383.27    29.3 1378.39      39 1373.85    48.8 1370.23
    54.5 1369.24    58.6 1368.52    68.3 1368.66    69.5 1368.89    78.1 1370.57
    87.8 1373.01    97.6 1375.23   107.3 1376.97   117.1 1377.94   136.6 1379.23
   146.4 1380.36   156.1 1382.68   165.9  1385.7   175.6 1387.58   185.4 1388.46
   195.2 1388.85   204.9 1390.23   214.7 1392.51   224.4 1395.34   234.2  1397.6
     244 1398.96   253.7 1399.97   273.2 1401.64     283 1402.38
#Mann= 3 , 0 , 0
       0      .1       0    54.5    .045       0    69.5      .1       0
Bank Sta=54.5,69.5
XS Rating Curve= 0 ,0
Exp/Cntr=0.3,0.1

Type RM Length L Ch R = 1 ,732.3   ,218.2,227.5,236.6
XS GIS Cut Line= 2
     1879427.726      346681.887     1879641.953      346690.813
#Sta/Elev= 25
       0 1395.33     9.8 1390.52    19.5 1385.88    29.2  1381.5      39  1377.4
    48.7 1373.61    58.5 1370.01    68.2 1366.57    70.1 1366.11      78 1364.21
    85.1 1363.84    87.7  1363.7    97.5 1365.34   107.2 1369.49     117 1374.24
   126.7 1376.75   136.4 1377.19   146.2 1376.85   155.9 1375.86   165.7 1374.14
   175.4 1372.16   185.2 1370.53   194.9 1369.49   204.7 1369.01   214.4 1369.09
#Mann= 3 , 0 , 0
       0      .1       0    70.1    .045       0    97.5      .1       0
#XS Ineff= 2 , 0
                          136.27         1377.43
Permanent Ineff=
       F       F
Bank Sta=70.1,97.5
XS Rating Curve= 0 ,0
Exp/Cntr=0.3,0.1

Type RM Length L Ch R = 1 ,504.9   ,231.1,249.5,268.1
XS GIS Cut Line= 2
     1879365.243      346858.178     1879597.322      346969.755
#Sta/Elev= 30
       0 1394.76     9.5 1389.57    19.1  1384.5    28.6 1379.42    38.2 1374.24
    47.7 1368.89    57.2 1362.55    66.8 1358.09    76.3 1356.32    85.8 1355.92
    95.4 1356.09   104.9 1356.58   107.8 1356.71   114.4    1357   122.8 1357.05
     124 1357.06   133.5 1357.38   143.1  1359.6   152.6 1364.35   162.1 1369.25
   171.7 1371.62   181.2 1371.98   190.8 1371.92   200.3 1371.67   209.8 1371.26
   219.4 1370.77   228.9 1370.24   238.4  1369.9     248 1369.22   257.5 1368.52
#Mann= 3 , 0 , 0
       0      .1       0    76.3    .045       0   114.4      .1       0
#XS Ineff= 2 , 0
                          181.27         1372.21
Permanent Ineff=
       F       F
Bank Sta=76.3,114.4
XS Rating Curve= 0 ,0
Exp/Cntr=0.3,0.1

Type RM Length L Ch R = 1 ,255.3   ,258,255.3,252.5
XS GIS Cut Line= 2
     1879226.888      346945.208     1879340.696      347302.253
#Sta/Elev= 26
       0 1380.67     9.6 1373.07    19.2 1365.76    28.8 1358.97    38.4 1353.91
      48  1351.2    57.6 1349.96    58.5 1349.93    67.3 1349.61    73.5 1350.29
    76.9 1350.67    96.1 1355.99   105.7 1356.92   163.4 1358.03   211.4 1359.54
     221 1359.99   230.6 1361.19   240.2 1363.28   249.8 1365.54   259.4 1367.37
     269 1368.67   278.7 1369.29   297.9 1369.57   326.7 1370.21   345.9 1370.29
   374.7 1370.96
#Mann= 3 , 0 , 0
       0      .1       0    58.5    .045       0    73.5      .1       0
Bank Sta=58.5,73.5
XS Rating Curve= 0 ,0
Exp/Cntr=0.3,0.1

Chan Stop Cuts=-1
Use User Specified Reach Order=0
Composite Channel Slope=5